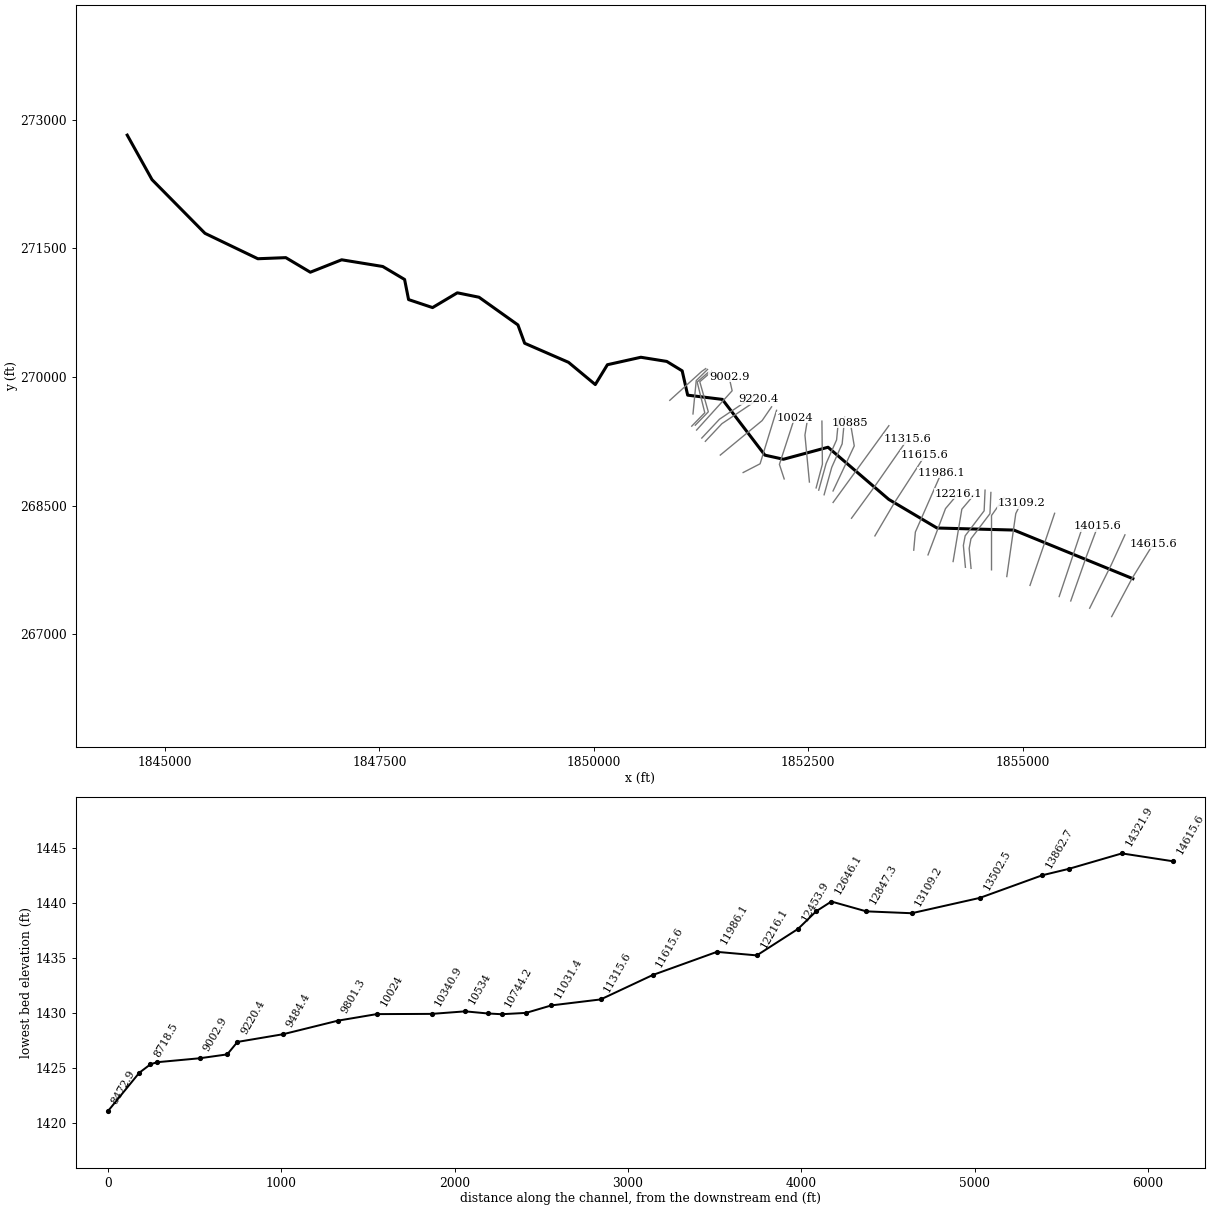
--- BIGCOVERN.prj (project) ---

Proj Title=BIGCOVERN
Current Plan=p01
Default Exp/Contr=0,0
English Units
Geom File=g01
Flow File=f01
Plan File=p01
BEGIN DESCRIPTION:
END DESCRIPTION:
DSS Export Rating Curves= 0
DSS Export Rating Curve Sorted= 0
DSS Export Volume Flow Curves= 0
DXF OffsetX= 0
DXF OffsetY= 0
DXF ScaleX= 0
DXF ScaleY= 0

--- BIGCOVERN.p01 (plan) ---

Plan Title=Floodplain
Program Version=4.00
Geom File=g01
Flow File=f01
K Sum by GR=0
Std Step Tol=0.01
Critical Tol=0.01
Num of Std Step Trials=20
Max Error Tol=0.3
Flow Tol Ratio=0.001
Split Flow NTrial=30
Split Flow Tol=0.02
Split Flow Ratio=0.02
Log Output Level=0
Friction Slope Method=1
Unsteady Friction Slope Method=2
Unsteady Bridges Friction Slope Method=1
Global Log Level=0
CheckData=False
Run HTab=0
Run UNet=0
Run PostProcess=0
UNET Theta=0
UNET Theta Warmup=0
UNET ZTol=0
UNET ZSATol=0
UNET MxIter=0
UNET MaxInSteps=0
UNET DtIC=0
UNET DtMin=0
UNET MaxCRTS=0
UNET WFStab=0
UNET SFStab=0
UNET WFX=0
UNET SFX=0
UNET DSS MLevel=0
UNET DZMax Abort=0
UNET Convert EG Bridges=0
UNET Use Existing IB Tables=0
UNET Froude Limit=0
UNET Froude Power=0
Write IC File=0
Echo Input=False
Echo Output=False
Write Detailed=0

--- BIGCOVERN.f01 (steady flow) ---

Flow Title=NFF Regression Equation
Program Version=4.10
Number of Profiles= 1
Profile Names=P100yr
River Rch & RM=BIGCOVERN,Main            ,14615.6
496.9231
River Rch & RM=BIGCOVERN,Main            ,14321.9
496.9858
River Rch & RM=BIGCOVERN,Main            ,14015.6
578.3612
River Rch & RM=BIGCOVERN,Main            ,12216.1
626.0313
River Rch & RM=BIGCOVERN,Main            ,10744.2
682.8233
River Rch & RM=BIGCOVERN,Main            ,9220.4
 756.284
River Rch & RM=BIGCOVERN,Main            ,5655.8
835.5481
River Rch & RM=BIGCOVERN,Main            ,428.3
922.8461
River Rch & RM=BIGCOVERN,Main            ,150.9
925.9051
Boundary for River Rch & Prof#=BIGCOVERN,Main            , 1
Up Type= 0
Dn Type= 3
Dn Slope=0.05623
DSS Import GetInterval= 0
DSS Import GetPeak= 0
DSS Import FillOption= 0

--- BIGCOVERN.g01 (geometry) ---

Geom Title=USGS 10m DEM
Program Version=4.10

River Reach=BIGCOVERN       ,Main
Reach XY= 30
     1856286.899      267650.538     1854898.683      268217.195
     1854002.762      268240.998     1853439.809      268574.659
     1852731.713      269182.304     1852211.739      269042.413
     1851995.473      269090.101      1851499.22      269740.043
     1851094.737       269789.31     1851030.748      270072.718
     1850850.814      270182.539     1850549.021      270231.002
     1850158.855      270144.033     1850017.456      269912.882
      1849705.26      270171.983     1849193.696      270394.345
     1849115.131      270608.035     1848661.494      270930.576
     1848408.558      270982.083     1848119.523      270809.934
     1847839.994      270903.207     1847793.549      271137.489
     1847539.024      271288.783     1847059.722      271366.938
     1846694.148      271222.084     1846408.267      271392.014
     1846082.147      271379.189     1845465.817      271675.146
     1844848.209      272300.595      1844558.93      272819.874

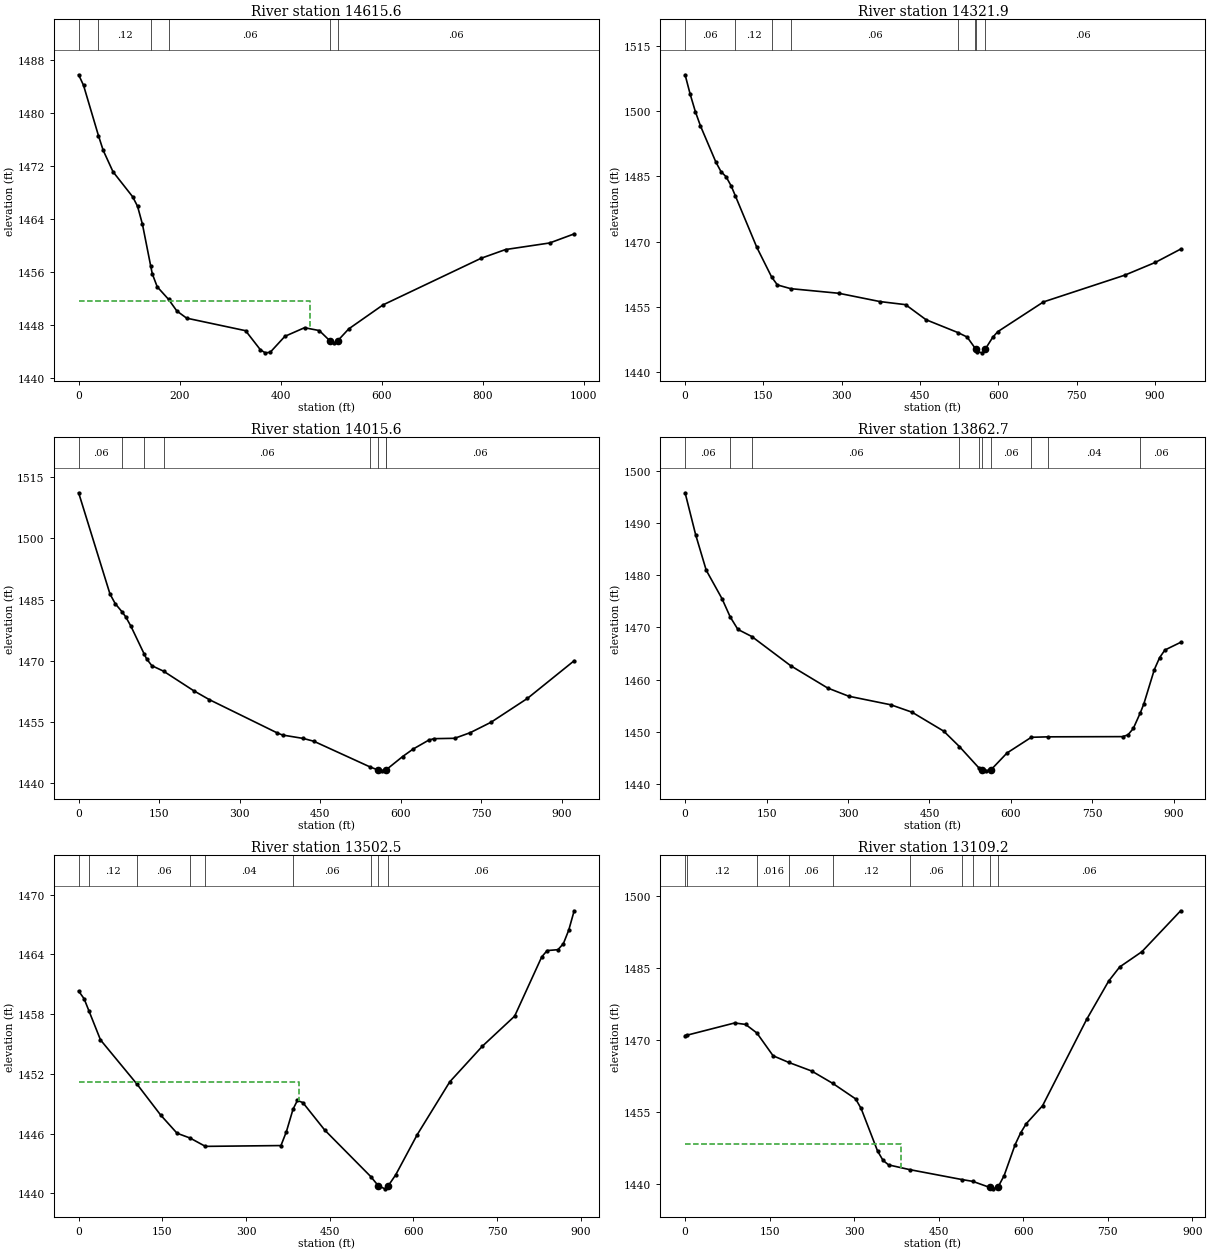
Type RM Length L Ch R = 1 ,14615.6 ,292.9,293.7,296.4
XS GIS Cut Line= 3
     1856039.414      267208.697     1856277.791      267654.668
     1856526.925      268059.641
#Sta/Elev= 30
       0  1485.7     9.7 1484.11   39.291476.508    48.6 1474.31    68.1 1471.07
     107  1467.3   116.7 1465.86   126.4 1463.14  142.881456.791   145.9 1455.67
   155.6 1453.72  178.161451.819   194.5 1450.07   213.9 1448.99   330.6  1447.1
   359.8 1444.23   369.5 1443.76   379.3 1443.84   408.4 1446.25   447.3 1447.55
   476.5 1447.12   498.2 1445.52   505.7 1445.18   513.2  1445.6   534.8 1447.37
   602.7 1450.99   796.8 1458.02   845.3 1459.34   932.6 1460.33   981.2  1461.7
#Mann= 6 ,-1 , 0
       0     .06       0   39.29     .12       0  142.88    .016       0
  178.16     .06       0   498.2    .045       0   513.2     .06       0
#XS Ineff= 2 , 0
          459.02 1451.55
Permanent Ineff=
       F       F
Bank Sta=498.2,513.2
XS Rating Curve= 0 ,0
Exp/Cntr=0.3,0.1

Type RM Length L Ch R = 1 ,14321.9 ,303.4,306.3,307.9
XS GIS Cut Line= 3
     1855782.913      267306.562     1856036.709      267816.307
     1856194.462      268161.452
#Sta/Elev= 30
       0  1508.3     9.8 1503.81    19.6 1499.86    29.4 1496.57    58.9 1488.27
    68.7 1486.08    78.5 1484.89    88.4 1482.75   96.49 1480.43   137.4 1468.67
  165.721461.873   176.7 1460.06  202.241459.203   294.5 1458.14   373.1 1456.24
   422.2 1455.53   461.4 1452.07  522.66 1449.11     540  1448.1  555.391445.533
   557.6 1445.25   559.6 1444.74   569.4 1444.47   574.3 1445.24   588.9    1448
   598.6 1449.32   686.2 1456.16   841.9  1462.3   900.3 1465.22   948.9 1468.28
#Mann= 8 ,-1 , 0
       0     .06       0   96.49     .12       0  165.72    .016       0
  202.24     .06       0  522.66     .12       0  555.39     .06       0
   557.6    .045       0   574.3     .06       0
Bank Sta=557.6,574.3
XS Rating Curve= 0 ,0
Exp/Cntr=0.3,0.1

Type RM Length L Ch R = 1 ,14015.6 ,152.5,152.9,153.7
XS GIS Cut Line= 3
     1855562.091      267390.814     1855749.921      267923.602
     1855876.132      268258.935
#Sta/Elev= 30
       0 1511.18    58.4 1486.39    68.2 1484.02   81.161481.978    87.7 1480.79
    97.4  1478.5  121.851471.763   126.6  1470.5   136.4 1468.83  158.281467.475
   214.3  1462.7   243.5 1460.51   370.1 1452.35   379.9 1451.84   418.8    1451
   438.3 1450.31  542.861444.029   557.4 1443.29   564.9 1443.07   572.4 1443.33
  573.231443.356   603.7 1446.58     623 1448.39   652.1 1450.58   661.8 1450.95
   700.5 1451.04   729.6 1452.42   768.3 1454.97   836.1 1460.81   923.2 1470.04
#Mann= 8 ,-1 , 0
       0     .06       0   81.16     .12       0  121.85    .016       0
  158.28     .06       0  542.86     .12       0   557.4    .045       0
   572.4     .12       0  573.23     .06       0
Bank Sta=557.4,572.4
XS Rating Curve= 0 ,0
Exp/Cntr=0.3,0.1

Type RM Length L Ch R = 1 ,13862.7 ,360.3,360.2,360.1
XS GIS Cut Line= 3
      1855427.32      267442.235     1855606.647      267976.723
     1855717.618      268307.477
#Sta/Elev= 30
       0 1495.81    19.4 1487.78    38.9 1480.96      68  1475.5   83.031472.012
    97.2 1469.61     1231468.238   194.4 1462.65   262.4 1458.38   301.3  1456.8
   379.1 1455.15     418 1453.73   476.3  1450.1  505.211447.142  540.471443.122
  546.39 1442.72     554 1442.49   563.8 1442.74   592.8 1445.91  637.571448.923
  668.56 1449.01     806 1449.05   815.7  1449.4   825.4 1450.61  838.411453.634
   844.8 1455.32   864.2 1461.92   873.9  1464.2   883.6 1465.66   912.6 1467.13
#Mann= 10 ,-1 , 0
       0     .06       0   83.03    .016       0     123     .06       0
  505.21     .12       0  540.47     .06       0  546.39    .045       0
   563.8     .06       0  637.57     .12       0  668.56     .04       0
  838.41     .06       0
Bank Sta=546.39,563.8
XS Rating Curve= 0 ,0
Exp/Cntr=0.3,0.1

Type RM Length L Ch R = 1 ,13502.5 ,389,393.3,397.4
XS GIS Cut Line= 3
     1855086.964      267572.093     1855262.548      268081.867
     1855374.239      268412.631
#Sta/Elev= 30
       0 1460.32     9.8 1459.55   18.771458.287    39.2 1455.41   104.71450.958
     147 1447.86   176.4 1446.03  199.791445.545   227.21444.709   362.7 1444.79
   372.5  1446.2  384.381448.453   392.1 1449.32   401.9 1449.11   441.1 1446.35
  523.631441.674  536.821440.773   548.9 1440.44   554.4  1440.7   568.3 1441.84
     607 1445.89   665.2 1451.19   723.4 1454.76   781.6  1457.8   830.1 1463.75
   839.8 1464.39   859.2 1464.48   868.9 1465.08   878.6 1466.45   888.3 1468.39
#Mann= 9 ,-1 , 0
       0    .016       0   18.77     .12       0   104.7     .06       0
  199.79     .08       0   227.2     .04       0  384.38     .06       0
  523.63     .12       0  536.82    .045       0   554.4     .06       0
#XS Ineff= 2 , 0
          394.57 1451.18
Permanent Ineff=
       F       F
Bank Sta=536.82,554.4
XS Rating Curve= 0 ,0
Exp/Cntr=0.3,0.1

Type RM Length L Ch R = 1 ,13109.2 ,258.8,262,265.1
XS GIS Cut Line= 3
     1854816.348      267675.344     1854921.203      268409.329
     1854982.131      268532.708
#Sta/Elev= 30
       0    1471    3.891471.099    87.8 1473.63   107.3 1473.33  127.271471.549
   156.1 1466.79  184.131465.392   224.4 1463.62  261.86 1461.04   302.4 1457.81
   312.2 1455.81   341.4 1446.93   351.2 1444.97     361 1444.04   398.21443.059
   491.41440.979  510.491440.601   540.2 1439.35   546.3 1439.05   555.2 1439.45
   565.8 1441.78   585.4 1448.26   595.1 1450.69   604.9  1452.6   634.1 1456.38
   712.2 1474.36   751.3 1482.36   770.9 1485.31   810.2 1488.48     879 1497.02
#Mann= 10 ,-1 , 0
       0    .016       0    3.89     .12       0  127.27    .016       0
  184.13     .06       0  261.86     .12       0   398.2     .06       0
   491.4     .12       0  510.49     .06       0   540.2    .045       0
   555.2     .06       0
#XS Ineff= 2 , 0
          383.83  1448.5
Permanent Ineff=
       F       F
Bank Sta=540.2,555.2
XS Rating Curve= 0 ,0
Exp/Cntr=0.3,0.1

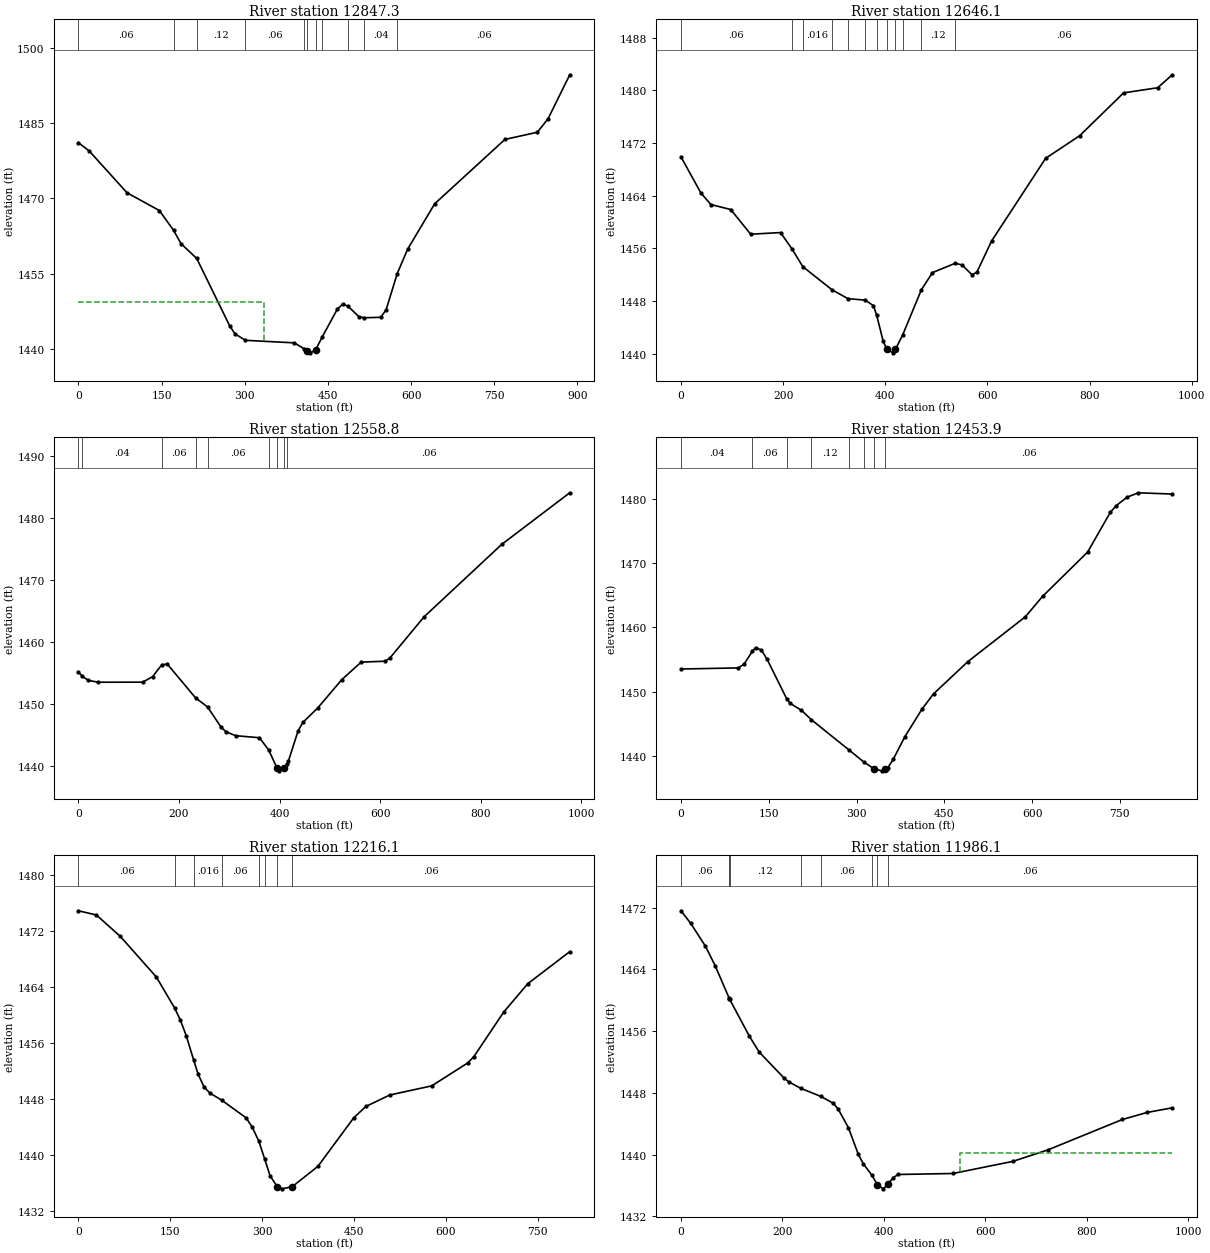
Type RM Length L Ch R = 1 ,12847.3 ,217.1,201.2,185.1
XS GIS Cut Line= 3
     1854638.217      267753.947     1854638.217       268386.76
     1854784.529      268593.687
#Sta/Elev= 30
       0 1481.09    19.5 1479.44    87.6 1471.12     146 1467.57  171.561463.644
     185 1460.98   213.41458.019   272.6 1444.65   282.3 1443.01  301.251441.714
   389.4 1441.21  406.611440.065   412.7  1439.6   418.6 1439.22   427.7 1439.79
  439.841442.409   467.3 1447.98     477 1448.93  486.441448.487   506.2 1446.39
  515.99 1446.21   545.2  1446.3   554.9 1447.77  575.061455.019   593.9 1459.89
   642.6 1468.92   769.3 1481.74   827.8 1483.17   847.2 1485.88   886.2 1494.62
#Mann= 11 ,-1 , 0
       0     .06       0  171.56    .016       0   213.4     .12       0
  301.25     .06       0  406.61     .12       0   412.7    .045       0
   427.7     .12       0  439.84     .06       0  486.44     .12       0
  515.99     .04       0  575.06     .06       0
#XS Ineff= 2 , 0
          334.09 1449.25
Permanent Ineff=
       F       F
Bank Sta=412.7,427.7
XS Rating Curve= 0 ,0
Exp/Cntr=0.3,0.1

Type RM Length L Ch R = 1 ,12646.1 ,87,87.3,87
XS GIS Cut Line= 5
      1854399.58      267770.907       1854377.8      268003.947
     1854398.634      268115.926     1854619.988      268407.593
     1854630.997      268655.308
#Sta/Elev= 30
       0 1469.88      39  1464.4    58.5 1462.64    97.5 1461.88   136.5 1458.13
     195 1458.38  216.961455.945  238.571453.205  295.561449.698  326.951448.345
   360.71448.114   376.9 1447.28  383.151445.841   396.1 1441.84  403.33 1440.63
   415.4 1440.11   419.8 1440.62  433.991442.796  470.571449.659   492.5  1452.3
  536.771453.709   550.3 1453.47   569.6 1451.99   579.2 1452.32   608.1 1457.08
   714.1 1469.66   780.9  1473.1   866.7  1479.6   933.5 1480.38   962.1 1482.35
#Mann= 12 ,-1 , 0
       0     .06       0  216.96     .12       0  238.57    .016       0
  295.56     .12       0  326.95     .06       0   360.7    .016       0
  383.15     .12       0  403.33    .045       0   419.8     .12       0
  433.99     .06       0  470.57     .12       0  536.77     .06       0
Bank Sta=403.33,419.8
XS Rating Curve= 0 ,0
Exp/Cntr=0.3,0.1

Type RM Length L Ch R = 1 ,12558.8 ,92.9,104.9,117.4
XS GIS Cut Line= 5
     1854333.865       267783.43     1854310.092      268037.801
     1854330.925       268149.78     1854552.279      268441.447
     1854562.997      268682.601
#Sta/Elev= 30
       0 1455.14    8.081454.464    19.6 1453.82    39.3 1453.52   127.7 1453.53
   147.4 1454.41  165.841456.349   176.9 1456.43  232.881450.997  256.761449.535
     284 1446.23   293.4 1445.54   312.4  1444.9   359.9 1444.57  378.171442.606
   394.6 1439.74   398.3 1439.23   409.6 1439.62  414.791440.398   417.6 1440.82
   436.8 1445.69   446.5 1447.06   475.4 1449.33   523.6 1453.93   562.1 1456.76
   610.3 1456.91   619.9 1457.48   687.4 1464.08   841.7 1475.75   976.9 1484.07
#Mann= 9 ,-1 , 0
       0     .06       0    8.08     .04       0  165.84     .06       0
  232.88    .016       0  256.76     .06       0  378.17     .12       0
   394.6    .045       0   409.6     .12       0  414.79     .06       0
Bank Sta=394.6,409.6
XS Rating Curve= 0 ,0
Exp/Cntr=0.3,0.1

Type RM Length L Ch R = 1 ,12453.9 ,242.2,237.8,233.4
XS GIS Cut Line= 3
       1854190.3      267850.301     1854291.863      268459.676
     1854435.092      268628.947
#Sta/Elev= 30
       0 1453.51    98.1 1453.68   107.9 1454.28  122.031456.286   127.5 1456.85
   137.3 1456.46   147.1 1455.04  180.541448.887   186.3 1448.17   205.9 1447.07
  222.711445.609  287.321440.871   312.31439.015  330.18 1437.93   343.2 1437.63
   349.1 1437.88     353 1438.05   362.8 1439.45   382.4 1442.93   411.8 1447.25
   431.5 1449.63   490.3 1454.67   588.4 1461.65   617.8 1464.83   694.9 1471.75
   733.5 1477.92   743.1 1478.94   762.4 1480.31   781.7 1480.99   839.5 1480.79
#Mann= 8 ,-1 , 0
       0     .04       0  122.03     .06       0  180.54    .016       0
  222.71     .12       0  287.32     .06       0   312.3     .12       0
  330.18    .045       0   349.1     .06       0
Bank Sta=330.18,349.1
XS Rating Curve= 0 ,0
Exp/Cntr=0.3,0.1

Type RM Length L Ch R = 1 ,12216.1 ,231.3,230.1,228.9
XS GIS Cut Line= 3
     1853897.621        267927.7     1854101.759      268467.489
     1854247.592      268639.364
#Sta/Elev= 30
       0 1474.87    29.3 1474.27    68.5 1471.21   127.2 1465.44  156.971461.035
   166.3 1459.34   176.1 1457.06  188.361453.552   195.6 1451.55   205.4 1449.73
   215.2 1448.85  233.731447.889   273.9 1445.35   283.7 1444.06  294.641442.031
  304.05 1439.53     313 1437.11  324.77 1435.52   332.6 1435.23  349.28 1435.54
   391.2 1438.44   449.9 1445.38   469.5 1446.97   508.6 1448.61   577.1 1449.91
   635.9 1453.18   645.7 1454.05   694.7 1460.44   733.9 1464.47   802.5 1469.04
#Mann= 8 ,-1 , 0
       0     .06       0  156.97     .12       0  188.36    .016       0
  233.73     .06       0  294.64     .12       0  304.05     .06       0
  324.77    .045       0  349.28     .06       0
Bank Sta=324.77,349.28
XS Rating Curve= 0 ,0
Exp/Cntr=0.3,0.1

Type RM Length L Ch R = 1 ,11986.1 ,373.1,370.5,366.8
XS GIS Cut Line= 3
     1853731.145      267982.755     1853750.196      268194.051
     1854054.722      268886.603
#Sta/Elev= 30
       0 1471.59    19.3 1469.95    48.2    1467    67.5 1464.46   94.791460.293
   95.611460.174   96.131460.099     135 1455.32   154.3 1453.27   202.5 1449.96
   212.2 1449.43  236.45 1448.57  276.17 1447.52   300.6 1446.63   310.4 1445.84
   330.1 1443.48   349.7 1440.01   359.5 1438.79   376.31437.329   387.1  1436.1
   398.8 1435.55   408.7  1436.2   418.5 1437.01   428.3 1437.41   536.4 1437.54
   654.3 1439.11   723.1 1440.59   870.4 1444.54   919.6 1445.46   968.7 1446.05
#Mann= 9 ,-1 , 0
       0     .06       0   94.79     .12       0   95.61     .06       0
   96.13     .12       0  236.45    .016       0  276.17     .06       0
   376.3     .12       0   387.1    .045       0   408.7     .06       0
#XS Ineff= 2 , 0
                          549.46         1440.24
Permanent Ineff=
       F       F
Bank Sta=387.1,408.7
XS Rating Curve= 0 ,0
Exp/Cntr=0.3,0.1

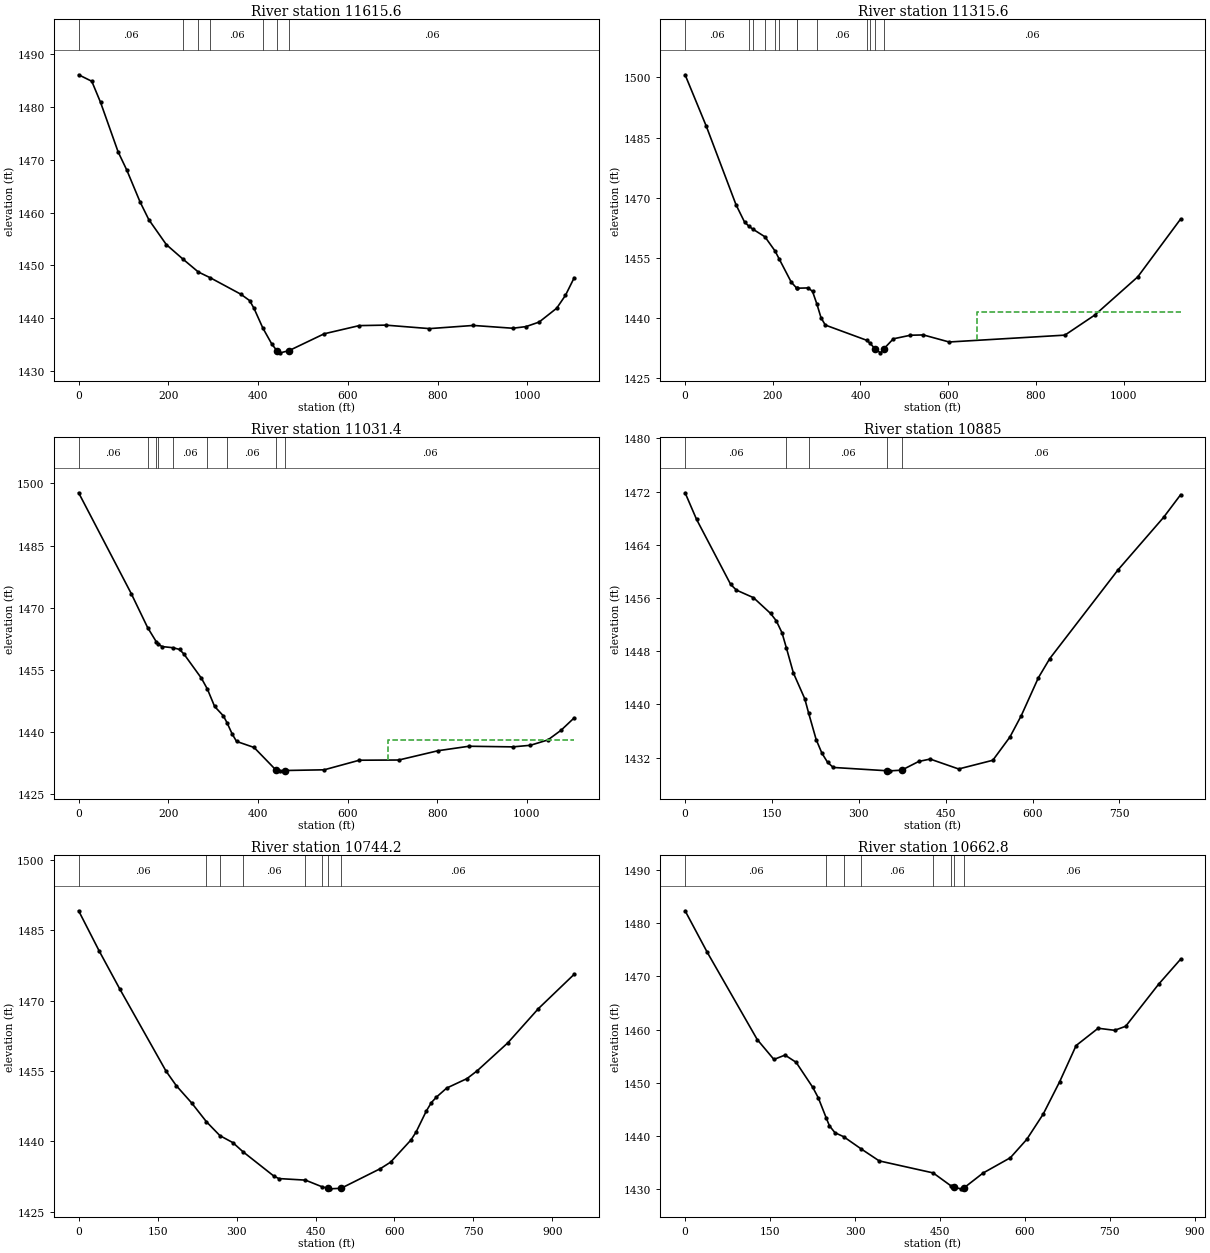
Type RM Length L Ch R = 1 ,11615.6 ,302.1,300,299.1
XS GIS Cut Line= 3
       1853278.2      268148.972     1853506.194      268536.399
     1853861.474      269086.322
#Sta/Elev= 30
       0 1486.13    29.3  1484.9    48.9 1480.89      88 1471.52   107.5 1468.04
   136.8 1462.06   156.4 1458.68   195.4 1453.96  232.811451.183  266.761448.765
   293.2 1447.68   361.6 1444.55   381.1 1443.34   390.9 1441.86  410.271438.184
     430 1435.18     442 1433.82   449.5 1433.45   469.1 1433.88   547.2 1437.06
   625.4 1438.61   684.1  1438.7   781.8 1438.04   879.5 1438.64   967.4 1438.11
   996.8 1438.42  1026.1 1439.28  1065.2  1441.9  1084.7 1444.33  1104.2 1447.67
#Mann= 7 ,-1 , 0
       0     .06       0  232.81     .12       0  266.76    .016       0
   293.2     .06       0  410.27     .12       0     442    .045       0
   469.1     .06       0
Bank Sta=442,469.1
XS Rating Curve= 0 ,0
Exp/Cntr=0.3,0.1

Type RM Length L Ch R = 1 ,11315.6 ,284.1,284.2,283.7
XS GIS Cut Line= 3
     1853005.542      268354.923     1853268.258      268714.843
      1853659.79      269276.322
#Sta/Elev= 30
       0 1500.67    48.4 1487.81   116.2  1468.2   135.6 1463.89  145.981462.815
  153.791462.178  182.111460.213  205.061456.684  214.811454.635   242.2 1448.87
  254.381447.415  255.291447.377   280.9 1447.45   290.6 1446.57  300.461443.462
     310    1440   319.7 1438.18  413.891434.387  421.181433.713  433.22 1432.23
   445.6 1431.24   453.1 1432.23   474.9 1434.74     514 1435.64   543.4 1435.71
   602.1 1433.95   866.1 1435.66   934.5 1440.69  1032.3 1450.21  1130.1 1464.66
#Mann= 13 ,-1 , 0
       0     .06       0  145.98     .12       0  153.79     .06       0
  182.11     .04       0  205.06     .06       0  214.81     .12       0
  254.38     .06       0  255.29    .016       0  300.46     .06       0
  413.89     .12       0  421.18     .06       0  433.22    .045       0
   453.1     .06       0
#XS Ineff= 2 , 0
                          664.78         1441.43
Permanent Ineff=
       F       F
Bank Sta=433.22,453.1
XS Rating Curve= 0 ,0
Exp/Cntr=0.3,0.1

Type RM Length L Ch R = 1 ,11031.4 ,142,146.5,150.9
XS GIS Cut Line= 2
     1852790.654      268538.892     1853440.918      269433.222
#Sta/Elev= 30
       0 1497.75   117.4 1473.44  153.871465.261  173.631461.756  178.011461.266
   185.9 1460.67  211.161460.381   225.1 1459.97   234.8 1458.89     274 1453.03
  287.331450.408   303.4 1446.23   322.9 1443.96  330.931442.338   342.5 1439.61
   352.3  1437.8   391.4 1436.34   440.2  1430.9   450.1  1430.7   459.9 1430.78
     548 1430.95   626.3 1433.26   714.3 1433.31   802.4 1435.56   870.9 1436.63
   968.8 1436.48  1007.9 1436.86    1047 1438.15  1076.4 1440.48  1105.7 1443.47
#Mann= 9 ,-1 , 0
       0     .06       0  153.87     .12       0  173.63     .08       0
  178.01     .12       0  211.16     .06       0  287.33    .016       0
  330.93     .06       0   440.2    .045       0   459.9     .06       0
#XS Ineff= 2 , 0
                          690.56         1438.17
Permanent Ineff=
       F       F
Bank Sta=440.2,459.9
XS Rating Curve= 0 ,0
Exp/Cntr=0.3,0.1

Type RM Length L Ch R = 1 ,10885   ,140.4,140.8,141.2
XS GIS Cut Line= 3
     1852790.127      268672.784     1853037.523      269197.957
      1852991.95      269469.225
#Sta/Elev= 30
       0 1471.82    19.7 1467.84    78.7 1458.04    88.6 1457.19   118.1 1456.05
   147.6 1453.68   157.4 1452.58   167.3 1450.78  174.971448.471     187 1444.73
   206.6 1440.86  213.281438.708   226.3 1434.72   236.2 1432.68     246  1431.3
   255.8 1430.53   348.9 1430.03   354.2 1430.02   373.9 1430.12   403.4 1431.43
   423.1 1431.79   472.3  1430.3   531.3 1431.61   560.8  1435.1   580.5 1438.33
     610 1444.02   629.6 1446.89   747.5 1460.23   826.1 1468.12   855.6 1471.53
#Mann= 5 ,-1 , 0
       0     .06       0  174.97    .016       0  213.28     .06       0
   348.9    .045       0   373.9     .06       0
Bank Sta=348.9,373.9
XS Rating Curve= 0 ,0
Exp/Cntr=0.3,0.1

Type RM Length L Ch R = 1 ,10744.2 ,81,81.3,81.3
XS GIS Cut Line= 4
     1852686.001      268628.487     1852774.936      268948.391
     1852896.463      269221.829     1852926.261      269530.422
#Sta/Elev= 30
       0 1489.18    39.1  1480.6    78.1 1472.52     166    1455   185.6 1451.88
   214.8  1448.2  242.881444.187  268.451441.234     293 1439.75     3121437.827
   370.6 1432.64   380.3 1432.09  430.831431.758  462.921430.314  473.96    1430
   476.8  1429.9   498.6 1430.02   573.4 1434.22   592.6 1435.59   631.3 1440.32
     641 1442.01   660.3 1446.46     670 1448.28   679.7 1449.46   699.1 1451.38
   737.8 1453.41   757.2 1455.08   815.3 1461.03   873.5 1468.34   941.3 1475.64
#Mann= 8 ,-1 , 0
       0     .06       0  242.88     .12       0  268.45    .016       0
     312     .06       0  430.83     .12       0  462.92     .06       0
  473.96    .045       0   498.6     .06       0
Bank Sta=473.96,498.6
XS Rating Curve= 0 ,0
Exp/Cntr=0.3,0.1

Type RM Length L Ch R = 1 ,10662.8 ,119.2,128.8,138.6
XS GIS Cut Line= 4
     1852623.179      268682.269     1852709.832      268993.964
     1852831.359      269267.402     1852855.632       269518.78
#Sta/Elev= 30
       0 1482.38    39.2 1474.54   127.4 1458.11   156.9 1454.36   176.5 1455.18
   196.1 1453.82   225.5  1449.1   235.3 1447.12  249.451443.289   254.9 1441.86
   264.7 1440.55  279.951439.804  310.471437.534   342.8 1435.24  438.151432.972
  470.241430.484  474.23 1430.26   487.6 1429.97   493.3 1430.21   526.2 1432.94
   574.5 1435.83   603.4 1439.28   632.5 1444.05   661.6 1450.16   690.7 1456.98
   729.6 1460.24   758.7 1459.85   778.2 1460.61   836.4 1468.54   875.3 1473.26
#Mann= 8 ,-1 , 0
       0     .06       0  249.45    .016       0  279.95     .12       0
  310.47     .06       0  438.15     .12       0  470.24     .06       0
  474.23    .045       0   493.3     .06       0
Bank Sta=474.23,493.3
XS Rating Curve= 0 ,0
Exp/Cntr=0.3,0.1

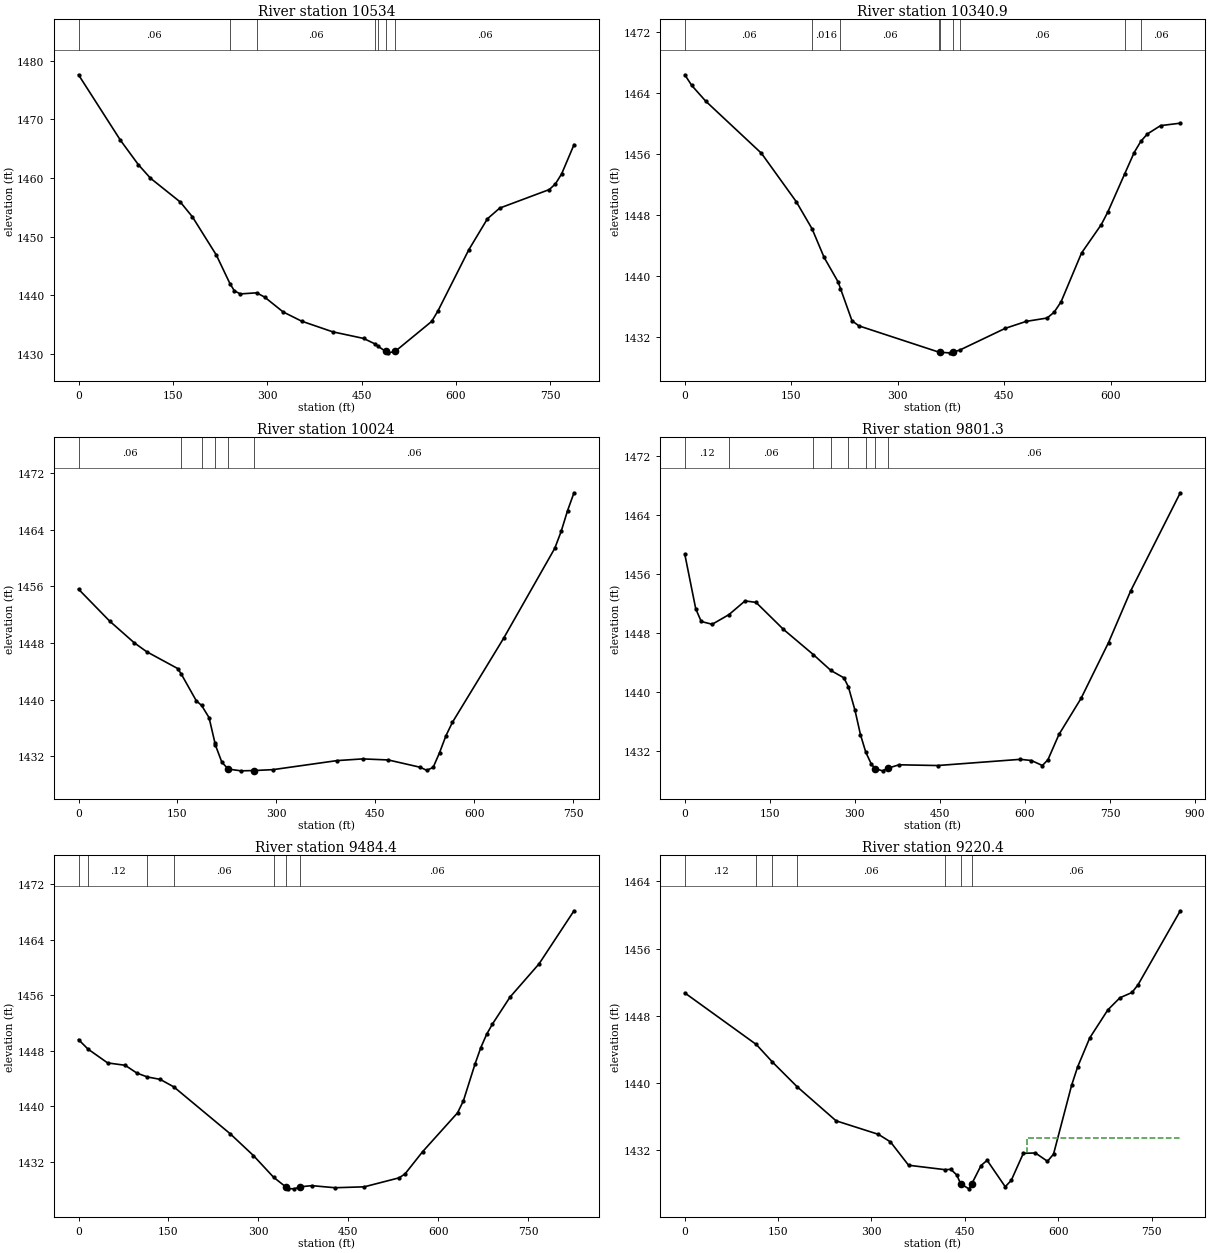
Type RM Length L Ch R = 1 ,10534   ,191,193.1,195.2
XS GIS Cut Line= 3
     1852592.717      268708.349     1852665.999      268984.729
     1852660.446      269486.606
#Sta/Elev= 30
       0 1477.59    66.7 1466.42    95.3 1462.24   114.4 1459.95     162 1455.87
   181.1 1453.36   219.2 1446.83  240.82 1441.96   247.8 1440.74   257.3 1440.21
  283.191440.398   295.8 1439.68   325.3 1437.14   354.8 1435.56     404 1433.75
   453.2 1432.62  471.071431.697  476.491431.262   488.4  1430.4   492.6 1430.16
   503.4  1430.4   561.5 1435.52   571.3 1437.27   620.5 1447.73   650.1 1453.02
   669.7 1454.85   748.5 1458.01   758.3 1458.98   768.2  1460.7   787.8 1465.66
#Mann= 7 ,-1 , 0
       0     .06       0  240.82    .016       0  283.19     .06       0
  471.07     .12       0  476.49     .06       0   488.4    .045       0
   503.4     .06       0
Bank Sta=488.4,503.4
XS Rating Curve= 0 ,0
Exp/Cntr=0.3,0.1

Type RM Length L Ch R = 1 ,10340.9 ,326.1,316.9,307.7
XS GIS Cut Line= 3
     1852514.519       268776.95     1852462.436      269323.825
     1852486.281      269470.148
#Sta/Elev= 30
       0 1466.35     9.8 1464.95    29.4  1462.9   107.9 1456.07     157 1449.72
  179.181446.175   196.2 1442.42   215.8 1439.23   219.21438.349   235.4 1434.13
   245.2 1433.46   357.51430.029   359.9 1429.99   372.8 1429.93  377.68 1430.01
  387.221430.297   451.2 1433.14   480.7 1434.05   510.1 1434.49   519.9 1435.24
   529.7  1436.6   558.6 1443.01   586.4 1446.73   595.7  1448.4  619.311453.368
   632.7 1456.17  642.151457.646   651.3  1458.6   669.8 1459.69   697.6 1460.01
#Mann= 9 ,-1 , 0
       0     .06       0  179.18    .016       0   219.2     .06       0
   357.5     .12       0   359.9    .045       0  377.68     .12       0
  387.22     .06       0  619.31     .12       0  642.15     .06       0
Bank Sta=359.9,377.68
XS Rating Curve= 0 ,0
Exp/Cntr=0.3,0.1

Type RM Length L Ch R = 1 ,10024   ,221.9,222.7,223.4
XS GIS Cut Line= 3
     1852220.451      268813.022     1852164.697      268982.559
     1852342.257      269526.946
#Sta/Elev= 30
       0 1455.62      47 1451.12    84.5 1448.03   103.3 1446.77   150.3 1444.39
  155.491443.656   178.5 1439.83  186.661439.157   197.9 1437.44  206.821433.854
   207.6 1433.54   217.3 1431.13     227 1430.16   246.4 1429.91   265.8 1429.95
   294.9 1430.08     392 1431.36   430.8  1431.6   469.6 1431.45   518.2 1430.41
   527.9 1429.98   537.6  1430.4   547.3 1432.48     557 1434.88   566.7 1436.76
   644.3 1448.65     722 1461.41   731.7 1463.81   741.4 1466.75   751.1 1469.26
#Mann= 6 ,-1 , 0
       0     .06       0  155.49     .12       0  186.66    .016       0
  206.82     .12       0     227    .045       0   265.8     .06       0
Bank Sta=227,265.8
XS Rating Curve= 0 ,0
Exp/Cntr=0.3,0.1

Type RM Length L Ch R = 1 ,9801.3  ,330.3,316.8,303.4
XS GIS Cut Line= 3
      1851741.95      268887.628     1851939.432      268989.624
     1852131.324      269612.333
#Sta/Elev= 30
       0 1458.69    19.3 1451.29      29 1449.57    48.3 1449.19   77.811450.496
   106.3 1452.36   125.6 1452.16     174  1448.5  226.951445.064   257.71442.926
   280.6 1441.93  288.461440.727   300.1 1437.55   309.8 1434.24  319.211431.844
   329.2  1430.2   335.8 1429.63   348.7 1429.32   358.4 1429.68   377.9 1430.14
     446 1430.04   591.8 1430.88   611.3 1430.72   630.7 1430.04   640.5 1430.83
   659.9 1434.25   698.8 1439.13   747.4 1446.72   786.3  1453.7   873.9 1467.02
#Mann= 8 ,-1 , 0
       0     .12       0   77.81     .06       0  226.95     .12       0
   257.7    .016       0  288.46     .06       0  319.21     .12       0
   335.8    .045       0   358.4     .06       0
Bank Sta=335.8,358.4
XS Rating Curve= 0 ,0
Exp/Cntr=0.3,0.1

Type RM Length L Ch R = 1 ,9484.4  ,266.2,264,261.7
XS GIS Cut Line= 3
     1851475.284      269091.026     1851963.304      269493.096
      1852073.48      269653.164
#Sta/Elev= 30
       0  1449.6   15.841448.235    48.6 1446.24    77.8  1445.9    97.3 1444.78
  114.571444.223   136.2 1443.87  159.061442.783   252.9 1436.04   291.8 1432.89
  325.421429.761   346.1 1428.35   350.2 1428.12   359.9 1428.09   369.7 1428.38
   389.1 1428.55     428 1428.25   476.7 1428.38     535 1429.68   544.8 1430.25
     574 1433.44   632.3 1439.04     642 1440.75   661.5 1446.09   671.2 1448.46
   680.9 1450.37   690.6 1451.85   719.8 1455.72   768.3 1460.52   826.6 1468.17
#Mann= 7 ,-1 , 0
       0    .016       0   15.84     .12       0  114.57    .016       0
  159.06     .06       0  325.42     .12       0   346.1    .045       0
   369.7     .06       0
Bank Sta=346.1,369.7
XS Rating Curve= 0 ,0
Exp/Cntr=0.3,0.1

Type RM Length L Ch R = 1 ,9220.4  ,59.3,59.1,59.3
XS GIS Cut Line= 3
     1851301.018      269251.412     1851494.059      269456.964
     1851921.142      269743.422
#Sta/Elev= 30
       0 1450.72   114.91444.579   140.91442.484  180.411439.556   243.1 1435.49
   311.1 1433.88   330.5 1432.98   359.6  1430.2  418.241429.672   427.5 1429.71
   437.2 1429.03  443.21 1427.99   456.6 1427.39   461.1 1427.98     476 1430.16
   485.8 1430.79   514.9 1427.64   524.6  1428.4     544 1431.62   563.4 1431.66
   582.8 1430.67   592.5 1431.52   621.6 1439.73   631.3 1441.92   650.7 1445.36
   679.8  1448.7   699.2 1450.14   718.6 1450.77   728.3 1451.69   796.2  1460.5
#Mann= 7 ,-1 , 0
       0     .12       0   114.9     .06       0   140.9    .016       0
  180.41     .06       0  418.24     .12       0  443.21    .045       0
   461.1     .06       0
#XS Ineff= 2 , 0
                          549.92          1433.5
Permanent Ineff=
       F       F
Bank Sta=443.21,461.1
XS Rating Curve= 0 ,0
Exp/Cntr=0.3,0.1

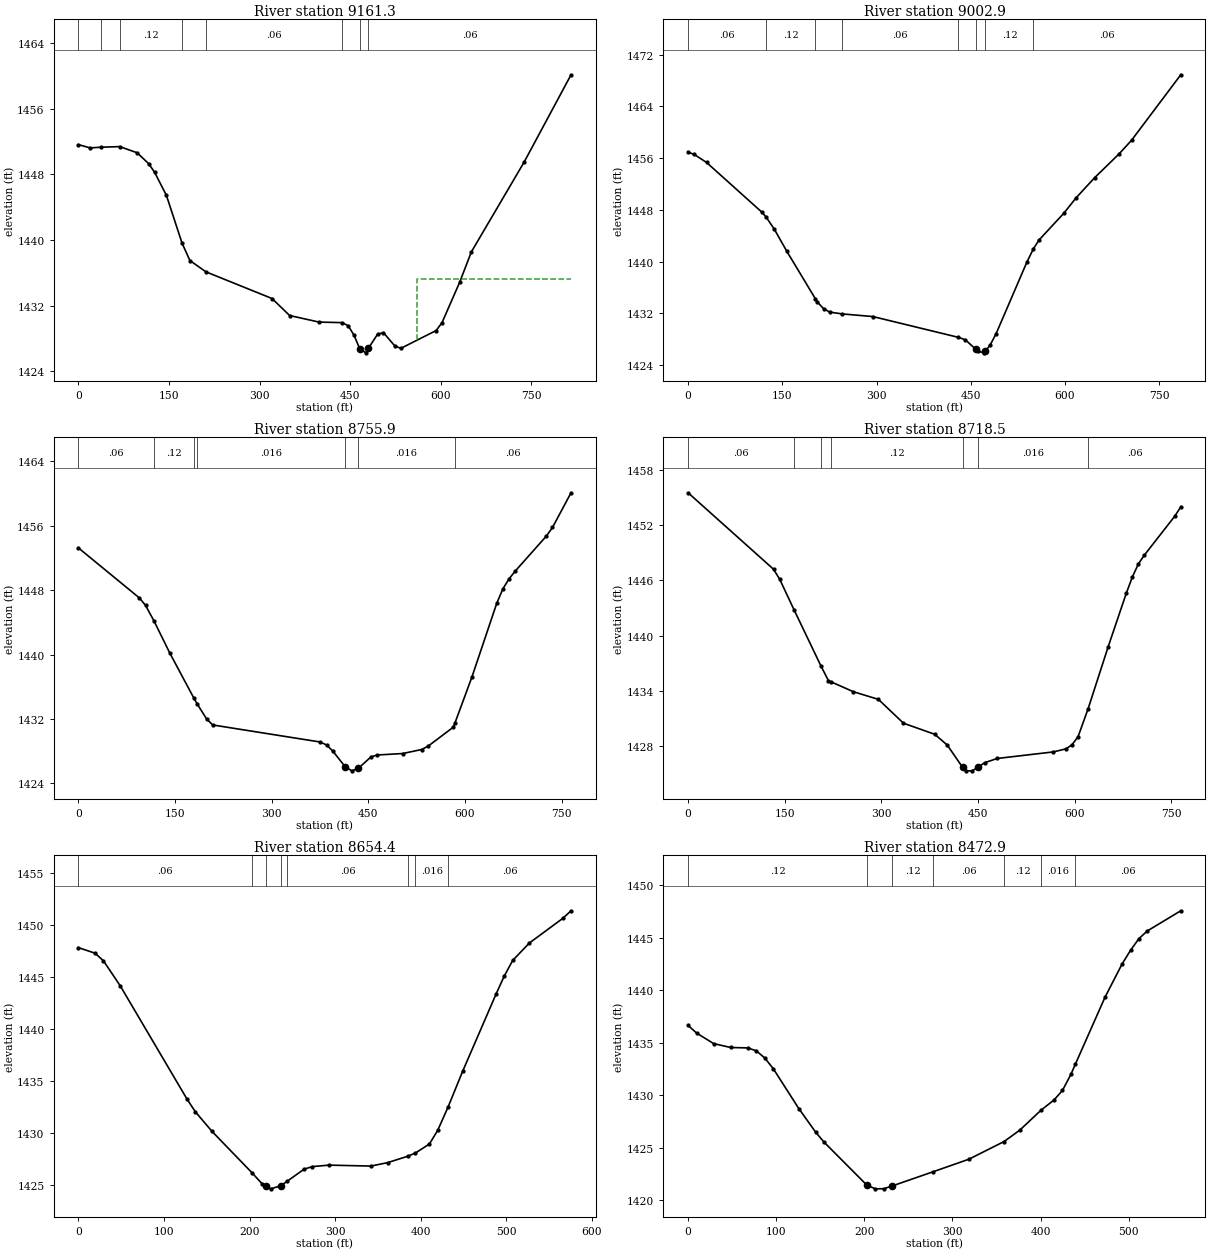
Type RM Length L Ch R = 1 ,9161.3  ,152.7,158.4,163.7
XS GIS Cut Line= 3
      1851259.65      269289.486     1851465.847      269509.047
     1851892.931      269795.505
#Sta/Elev= 30
       0 1451.64    19.4 1451.24   38.231451.324    68.41451.395    97.2 1450.65
   116.6  1449.3   126.3 1448.25   145.7 1445.46  171.611439.635   184.6 1437.51
  211.161436.132   320.6 1432.88   349.7 1430.81   398.2 1430.01  436.891429.941
   446.8 1429.55   456.4 1428.39  465.72 1426.76   475.9 1426.26  480.01 1426.81
   495.3 1428.53     505 1428.72   524.4 1427.05   534.1 1426.82   592.3 1428.98
     602 1429.95   631.1 1434.85   650.5 1438.56   737.8  1449.5   815.5 1460.15
#Mann= 8 ,-1 , 0
       0     .12       0   38.23     .06       0    68.4     .12       0
  171.61    .016       0  211.16     .06       0  436.89     .12       0
  465.72    .045       0  480.01     .06       0
#XS Ineff= 2 , 0
                          561.33         1435.25
Permanent Ineff=
       F       F
Bank Sta=465.72,480.01
XS Rating Curve= 0 ,0
Exp/Cntr=0.3,0.1

Type RM Length L Ch R = 1 ,9002.9  ,223.6,247,270
XS GIS Cut Line= 3
      1851198.92      269382.745     1851613.417      269840.644
     1851576.923      270003.205
#Sta/Elev= 30
       0 1456.94     9.8 1456.58    29.4 1455.34   117.6 1447.64  124.291446.882
   137.2 1445.03   156.9 1441.64  202.471434.289   205.9 1433.75   215.7 1432.73
   225.5 1432.21  245.251431.928   294.1 1431.52  430.061428.308   441.2 1427.93
   458.3 1426.43   460.8  1426.2   470.6 1425.91   473.3 1426.22   480.4 1427.05
   490.2 1428.86   539.2 1439.93  549.67 1442.01   558.8 1443.38     598 1447.49
   617.6 1449.88     647 1452.98   686.2 1456.69   705.8 1458.77   784.2  1468.9
#Mann= 8 ,-1 , 0
       0     .06       0  124.29     .12       0  202.47    .016       0
  245.25     .06       0  430.06     .12       0   458.3    .045       0
   473.3     .12       0  549.67     .06       0
Bank Sta=458.3,473.3
XS Rating Curve= 0 ,0
Exp/Cntr=0.3,0.1

Type RM Length L Ch R = 1 ,8755.9  ,38.4,37.4,36.7
XS GIS Cut Line= 4
     1851183.729      269439.168     1851335.639      269595.418
     1851236.095      269945.667     1851374.437      270064.842
#Sta/Elev= 30
       0 1453.25    94.8 1447.02   104.2 1446.11  117.281444.181   142.1 1440.15
  178.851434.646  184.681433.825     199    1432   208.4 1431.25   375.4 1429.13
   385.2 1428.76   395.1 1427.99   414.3 1426.03   424.6 1425.55   434.4 1425.85
   454.1 1427.28     464 1427.52   503.3  1427.7   532.8  1428.2   542.7 1428.61
     582 1430.98  584.291431.457   610.9 1437.23   649.3 1446.36   658.9 1448.17
   668.5 1449.41   678.2 1450.38   726.2  1454.7   735.8 1455.78   764.6 1460.09
#Mann= 7 ,-1 , 0
       0     .06       0  117.28     .12       0  178.85     .06       0
  184.68    .016       0   414.3    .045       0   434.4    .016       0
  584.29     .06       0
Bank Sta=414.3,434.4
XS Rating Curve= 0 ,0
Exp/Cntr=0.3,0.1

Type RM Length L Ch R = 1 ,8718.5  ,72.2,64.1,56.4
XS GIS Cut Line= 4
     1851142.496      269428.318     1851294.406      269584.568
     1851205.713      269942.411     1851339.979      270059.828
#Sta/Elev= 30
       0 1455.48   132.6  1447.2   142.1 1446.13  164.811442.754  206.521436.682
   217.9 1435.13  221.591435.008   256.7 1433.93   295.5  1433.1   334.4 1430.52
   382.9 1429.32   402.3 1428.16   426.1 1425.75   431.4 1425.36   441.1 1425.36
   450.8 1425.78   460.5 1426.24   479.9  1426.7   567.2 1427.41   586.6 1427.74
     596 1428.18   605.4 1429.04  621.121432.088   652.3 1438.81   680.5 1444.62
   689.9 1446.37   699.2 1447.78   708.6 1448.74   755.6 1452.94     765 1453.95
#Mann= 7 ,-1 , 0
       0     .06       0  164.81     .12       0  206.52     .06       0
  221.59     .12       0   426.1    .045       0   450.8    .016       0
  621.12     .06       0
Bank Sta=426.1,450.8
XS Rating Curve= 0 ,0
Exp/Cntr=0.3,0.1

Type RM Length L Ch R = 1 ,8654.4  ,197.8,181.5,164
XS GIS Cut Line= 3
     1851156.711      269570.353     1851194.645      269959.122
     1851326.474      270088.824
#Sta/Elev= 30
       0  1447.8    19.5 1447.26    29.3 1446.53    48.8 1444.14     127 1433.22
   136.7 1432.01   156.2 1430.12  202.911426.141   214.8 1425.07  218.89 1424.85
   224.6  1424.6  236.53 1424.89     2441425.334   263.7 1426.49   273.4 1426.74
     293 1426.88   341.8 1426.79   361.3 1427.12   384.91427.737  393.771428.042
   410.1 1428.91   419.8 1430.22  431.761432.431     449 1435.91     488 1443.33
   497.7 1445.08   507.4 1446.56   526.9 1448.24   565.8  1450.6   575.6 1451.34
#Mann= 8 ,-1 , 0
       0     .06       0  202.91     .12       0  218.89    .045       0
  236.53     .12       0     244     .06       0   384.9     .12       0
  393.77    .016       0  431.76     .06       0
Bank Sta=218.89,236.53
XS Rating Curve= 0 ,0
Exp/Cntr=0.3,0.1

Type RM Length L Ch R = 1 ,8472.9  ,237.7,245,250.7
XS GIS Cut Line= 3
     1850886.139      269728.824     1851258.382      270065.904
     1851305.257      270098.457
#Sta/Elev= 30
       0 1436.67     9.7 1435.94      29 1434.94    48.3 1434.57    67.6 1434.53
    77.3 1434.26    86.9 1433.58    96.6 1432.56   125.6 1428.76   144.9 1426.49
   154.5 1425.54   202.8 1421.47   212.5 1421.11   222.1 1421.12   231.8 1421.39
  277.911422.732   318.7 1423.93  358.671425.616   376.6 1426.71  400.461428.592
   415.3 1429.57   424.9 1430.48   434.6 1432.03  439.421432.959   473.2 1439.36
   492.5 1442.51   502.2 1443.83   511.7 1444.94   521.2 1445.67   559.2 1447.59
#Mann= 7 ,-1 , 0
       0     .12       0   202.8    .045       0   231.8     .12       0
  277.91     .06       0  358.67     .12       0  400.46    .016       0
  439.42     .06       0
Bank Sta=202.8,231.8
XS Rating Curve= 0 ,0
Exp/Cntr=0.3,0.1