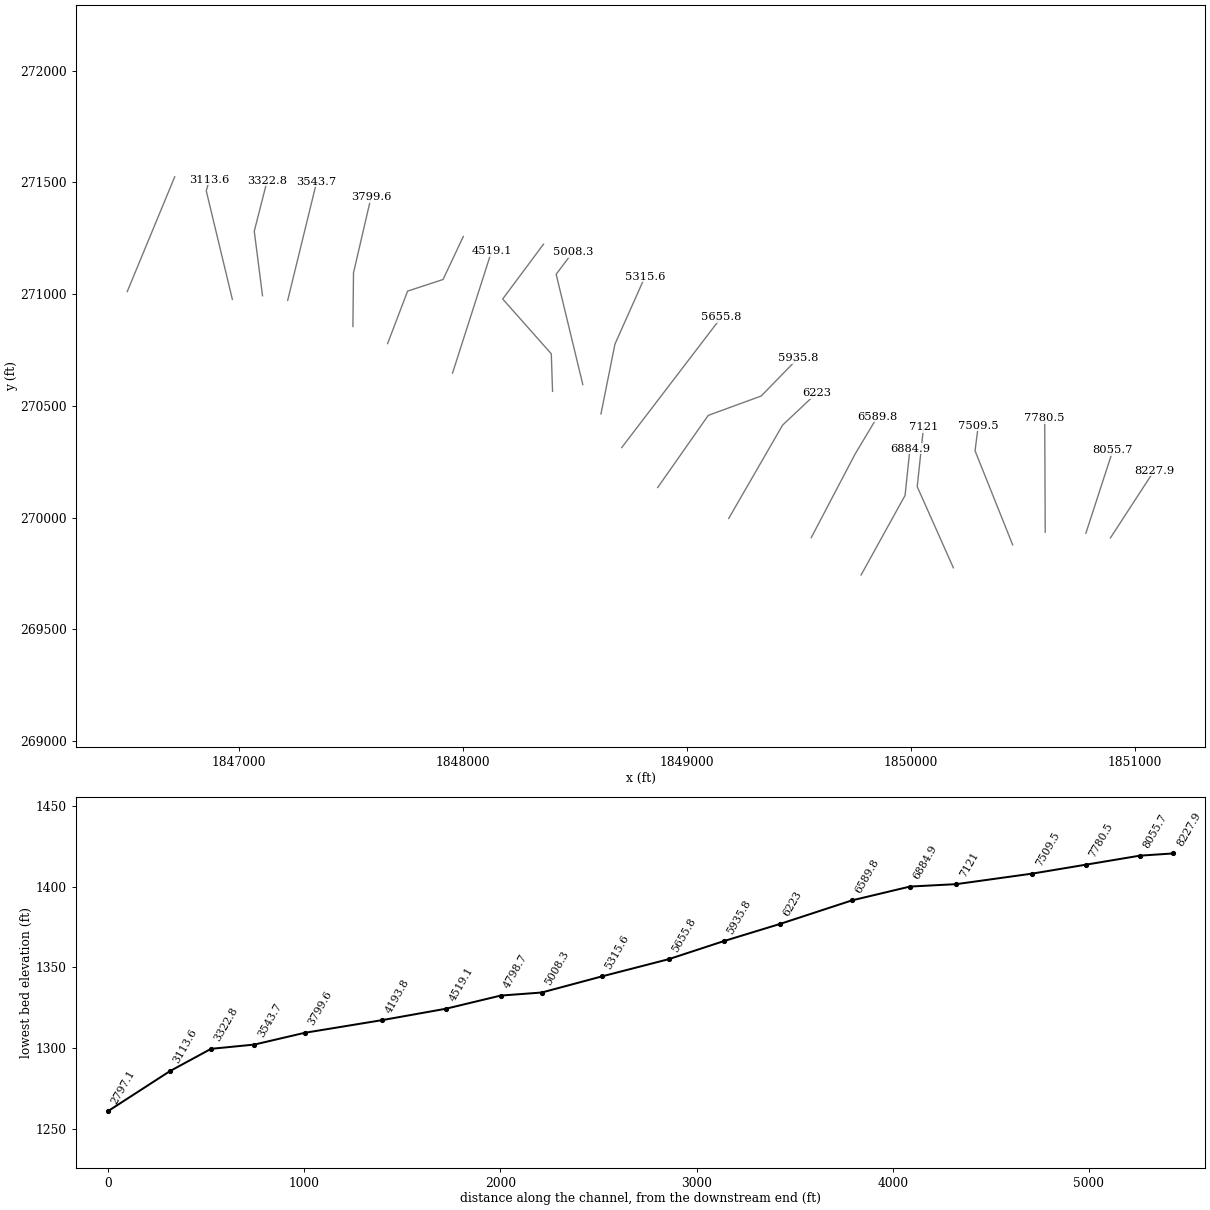
HEC-RAS study BIGCOVERN.prj: BIGCOVERN

--- BIGCOVERN.g01 (geometry) --- (continued)

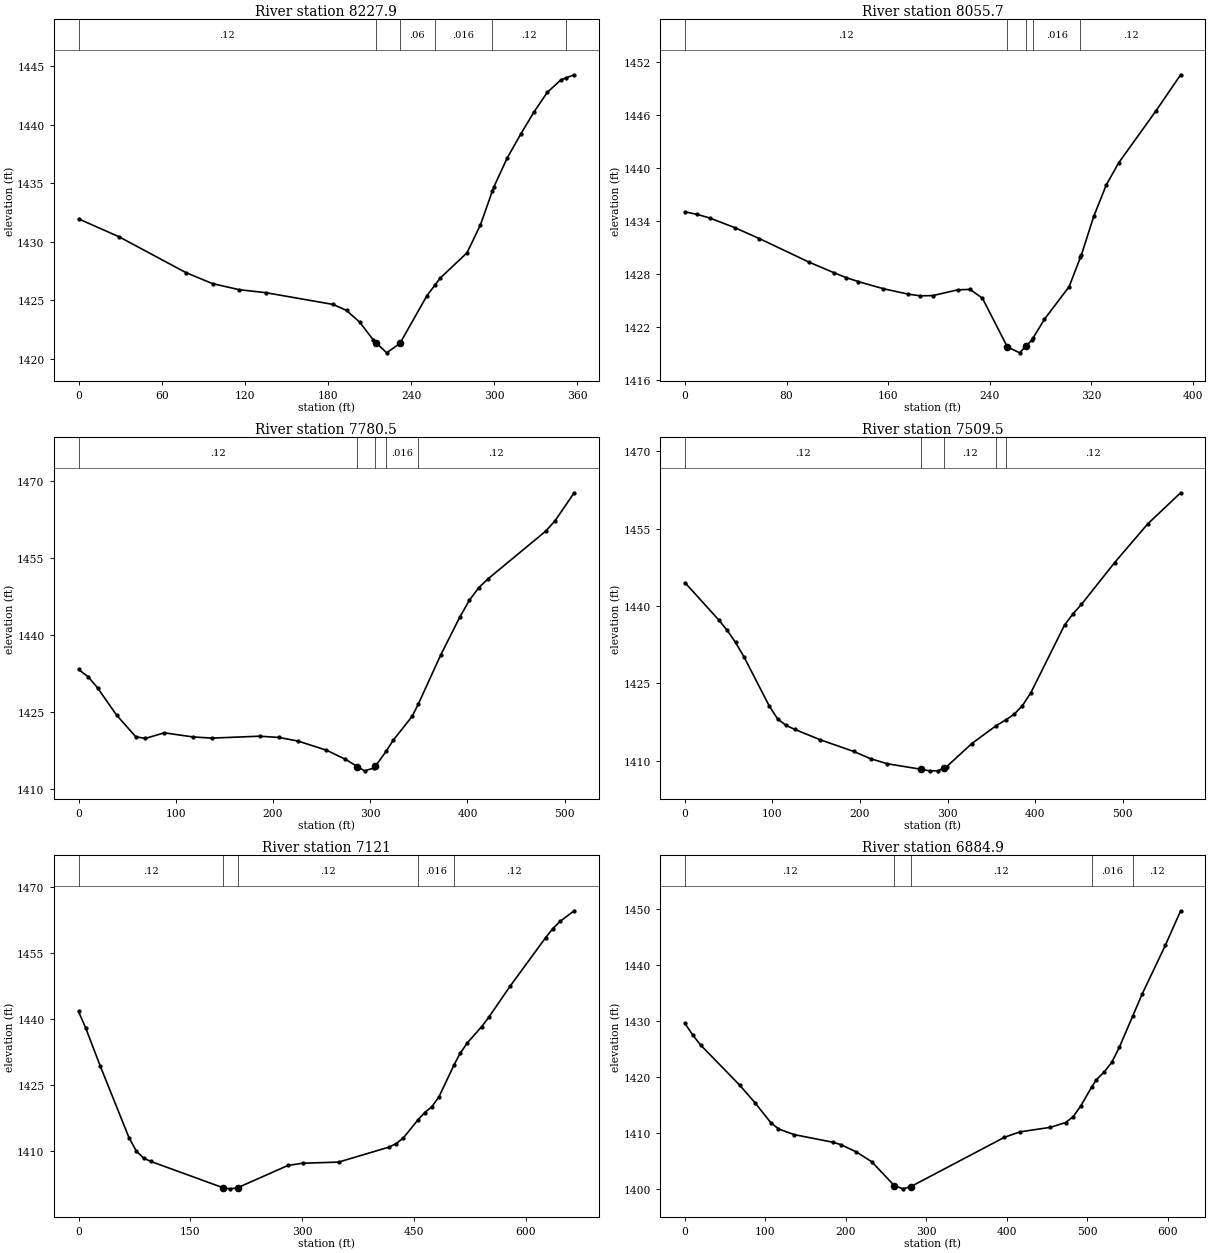
Type RM Length L Ch R = 1 ,8227.9  ,166.5,172.2,178.1
XS GIS Cut Line= 2
      1850890.76       269909.22     1851085.492      270209.314
#Sta/Elev= 27
       0 1431.97      29 1430.45    77.4 1427.38    96.7 1426.43     116 1425.91
   135.4 1425.65   183.7 1424.65   193.4 1424.14     203 1423.12   212.7 1421.62
   214.7 1421.39   222.4 1420.51     232 1421.32   251.4 1425.39  257.041426.277
     261  1426.9   280.4 1429.07   290.1 1431.47   298.61434.321   299.7 1434.69
   309.4 1437.18   319.1 1439.21   328.7 1441.11   338.4  1442.8   348.1 1443.85
  352.03 1444.03   357.7 1444.29
#Mann= 6 ,-1 , 0
       0     .12       0   214.7    .045       0     232     .06       0
  257.04    .016       0   298.6     .12       0  352.03    .016       0
Bank Sta=214.7,232
XS Rating Curve= 0 ,0
Exp/Cntr=0.3,0.1

Type RM Length L Ch R = 1 ,8055.7  ,267.5,275.2,282.1
XS GIS Cut Line= 2
     1850780.951      269930.054     1850901.627      270301.247
#Sta/Elev= 30
       0 1435.06     9.8 1434.76    19.5 1434.36      39 1433.28    58.6 1432.03
    97.6 1429.37   117.1 1428.18   126.8 1427.62   136.6 1427.16   156.1 1426.36
   175.6 1425.75   185.4 1425.55   195.2 1425.58   214.7 1426.23   224.4 1426.28
   234.2 1425.29   253.8 1419.79   263.5  1419.1   268.8  1419.9   273.2 1420.56
  274.171420.791     283 1422.89   302.5 1426.59   311.41429.911   312.2 1430.21
     322 1434.59   331.8 1438.12   341.5  1440.6   370.8 1446.47   390.3 1450.57
#Mann= 5 ,-1 , 0
       0     .12       0   253.8    .045       0   268.8     .12       0
  274.17    .016       0   311.4     .12       0
Bank Sta=253.8,268.8
XS Rating Curve= 0 ,0
Exp/Cntr=0.3,0.1

Type RM Length L Ch R = 1 ,7780.5  ,262.4,271,279.4
XS GIS Cut Line= 2
     1850599.411      269934.486     1850597.125      270444.192
#Sta/Elev= 30
       0 1433.26     9.8 1431.87    19.6 1429.68    39.2 1424.36    58.8 1420.17
    68.6 1419.82    88.2 1420.92   117.6 1420.12   137.2 1419.89   186.2 1420.26
   205.8 1420.02   225.4 1419.33   254.9 1417.54   274.5 1415.76  286.77 1414.33
   294.1 1413.51   303.9 1414.06  305.17 1414.36  316.711417.424   323.5 1419.44
   343.1 1424.14  349.281426.467   372.5  1436.1   392.1 1443.47   401.9 1446.74
   411.7 1449.23   421.5 1450.99   480.3  1460.2   490.1 1462.26   509.7  1467.7
#Mann= 5 ,-1 , 0
       0     .12       0  286.77    .045       0  305.17     .12       0
  316.71    .016       0  349.28     .12       0
Bank Sta=286.77,305.17
XS Rating Curve= 0 ,0
Exp/Cntr=0.3,0.1

Type RM Length L Ch R = 1 ,7509.5  ,388.1,388.5,386.9
XS GIS Cut Line= 3
     1850453.992      269878.029     1850286.051      270298.869
      1850300.35      270411.217
#Sta/Elev= 30
       0 1444.54    38.6  1437.3    48.2 1435.29    57.8 1432.93    67.5 1430.12
    96.4 1420.58     106 1418.06   115.7 1416.84   125.3 1416.08   154.2 1414.08
   192.8 1411.79   212.1 1410.38   231.4  1409.4   269.9 1408.33   279.6 1408.03
   289.2 1408.04     296 1408.59   298.9 1408.82   327.8 1413.33  355.741416.803
  366.321417.882     376 1418.98   385.6 1420.67   395.3  1423.2   433.8 1436.32
   443.5 1438.51   453.1 1440.33   490.9 1448.41   528.6  1455.9   566.4 1461.97
#Mann= 5 ,-1 , 0
       0     .12       0   269.9    .045       0     296     .12       0
  355.74    .016       0  366.32     .12       0
Bank Sta=269.9,296
XS Rating Curve= 0 ,0
Exp/Cntr=0.3,0.1

Type RM Length L Ch R = 1 ,7121    ,255.8,236.1,218.1
XS GIS Cut Line= 3
     1850189.166      269775.215     1850027.805      270138.279
      1850055.99       270404.03
#Sta/Elev= 30
       0  1441.8     9.7 1438.02    29.1 1429.42    67.8 1413.08    77.5 1410.08
    87.2 1408.48    96.9 1407.72   193.8 1401.74   203.5 1401.49   213.2 1401.73
     281 1406.82   300.4 1407.31   348.8 1407.57   416.4 1410.98   425.9 1411.77
   435.5 1413.05  455.43 1417.23   464.1  1418.8   473.7 1420.14   483.2 1422.37
  503.57 1429.67   511.8 1432.33   521.4 1434.67   540.5 1438.34     550 1440.46
   578.6 1447.53   626.4  1458.6   635.9 1460.62   645.5 1462.26   664.6 1464.69
#Mann= 5 ,-1 , 0
       0     .12       0   193.8    .045       0   213.2     .12       0
  455.43    .016       0  503.57     .12       0
Bank Sta=193.8,213.2
XS Rating Curve= 0 ,0
Exp/Cntr=0.3,0.1

Type RM Length L Ch R = 1 ,6884.9  ,294.9,295.1,295.7
XS GIS Cut Line= 3
     1849777.201      269743.217     1849973.551      270099.216
     1849995.253      270307.549
#Sta/Elev= 30
       0 1429.54     9.7 1427.46    19.4 1425.68    67.8 1418.54    87.1 1415.36
   106.5 1411.84   116.2  1410.7   135.5 1409.68   183.9 1408.31   193.6 1407.89
     213 1406.58   232.3 1404.81     260 1400.58     271 1399.99   280.7 1400.39
   396.9 1409.19   416.1 1410.16   454.2 1410.98   473.2 1411.84   482.7 1412.91
   492.2 1414.87  505.761418.261   511.3 1419.48   520.8 1420.83   530.3 1422.57
   539.8 1425.26   556.71430.949   568.4 1434.85     597 1443.49     616 1449.66
#Mann= 5 ,-1 , 0
       0     .12       0     260    .045       0   280.7     .12       0
  505.76    .016       0   556.7     .12       0
Bank Sta=260,280.7
XS Rating Curve= 0 ,0
Exp/Cntr=0.3,0.1

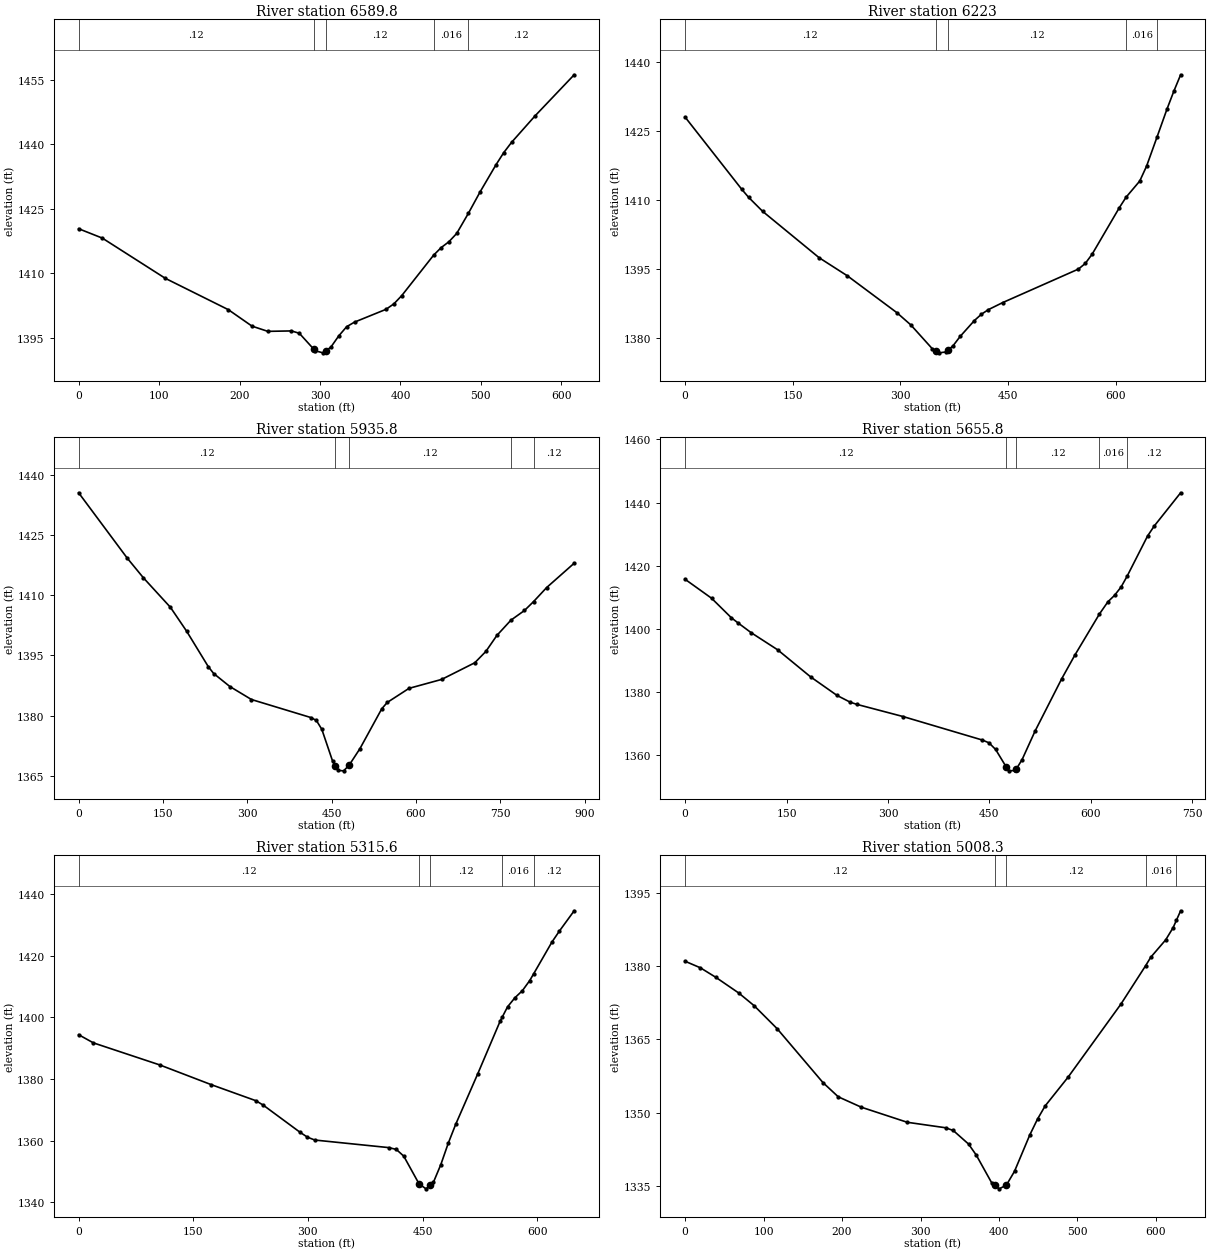
Type RM Length L Ch R = 1 ,6589.8  ,367.3,366.8,365.3
XS GIS Cut Line= 3
     1849554.714      269910.414     1849750.027      270283.678
     1849849.853      270450.779
#Sta/Elev= 30
       0 1420.33    29.4 1418.15   107.8 1408.78   186.1 1401.49   215.5 1397.66
   235.1 1396.45   264.5 1396.55   274.3    1396   292.2 1392.31   293.9 1391.94
   303.7 1391.45   307.2 1391.92   313.5 1392.78   323.3 1395.39   333.1 1397.53
   342.9  1398.6   382.1 1401.58   391.9 1402.86   401.7 1404.79  441.171414.168
   450.5 1415.92   460.2  1417.3   469.9 1419.23  484.481423.935   499.1 1428.94
   518.6 1435.17   528.3 1438.02   538.1 1440.43   567.3 1446.59   615.9 1456.15
#Mann= 5 ,-1 , 0
       0     .12       0   292.2    .045       0   307.2     .12       0
  441.17    .016       0  484.48     .12       0
Bank Sta=292.2,307.2
XS Rating Curve= 0 ,0
Exp/Cntr=0.3,0.1

Type RM Length L Ch R = 1 ,6223    ,302.7,287.2,271
XS GIS Cut Line= 3
     1849186.148      269996.409     1849426.676      270413.886
     1849578.586      270557.115
#Sta/Elev= 30
       0    1428    78.7 1412.39    88.5  1410.6   108.2 1407.54   186.8  1397.5
   226.2 1393.57     295  1385.6   314.6 1382.92   344.2 1377.81   349.3 1377.32
     354 1376.87   363.8 1377.07  366.27 1377.39   373.6 1378.44   383.5 1380.46
   403.2 1383.88     413 1385.25   422.8 1386.25   442.5 1387.76   548.2 1395.04
   557.7 1396.26   567.2 1398.25   605.2 1408.36  614.561410.626   633.6 1414.13
   643.1 1417.35  657.861423.747   671.6 1429.75   681.1 1433.61   690.6 1437.18
#Mann= 5 ,-1 , 0
       0     .12       0   349.3    .045       0  366.27     .12       0
  614.56    .016       0  657.86     .12       0
Bank Sta=349.3,366.27
XS Rating Curve= 0 ,0
Exp/Cntr=0.3,0.1

Type RM Length L Ch R = 1 ,5935.8  ,267.1,280.1,292.8
XS GIS Cut Line= 4
     1848868.919      270134.557     1849094.645      270457.289
      1849331.19      270544.095      1849495.42       270713.11
#Sta/Elev= 30
       0 1435.52    86.4 1419.24   115.3 1414.31   163.3 1406.97   192.1 1401.02
   230.5 1392.21   240.2 1390.47     269 1387.23   307.4 1383.99   413.2 1379.49
   422.9 1378.77   432.6 1376.56     452 1368.54   456.8 1367.44   461.7 1366.31
   471.4 1366.21   481.1  1367.6   500.4 1371.74   539.2 1381.67   548.9 1383.25
   587.7 1386.77   645.8    1389   704.7 1393.15   724.4 1395.97     744 1399.96
  769.011403.769   793.1 1406.18  809.431408.419   832.4 1411.88   881.5 1417.96
#Mann= 5 ,-1 , 0
       0     .12       0   456.8    .045       0   481.1     .12       0
  769.01    .016       0  809.43     .12       0
Bank Sta=456.8,481.1
XS Rating Curve= 0 ,0
Exp/Cntr=0.3,0.1

Type RM Length L Ch R = 1 ,5655.8  ,334.9,340.2,345.4
XS GIS Cut Line= 2
     1848708.233      270313.302     1849152.539      270895.979
#Sta/Elev= 30
       0 1415.72    39.1 1409.73    68.4 1403.54    78.2 1401.92    97.7 1398.81
   136.8  1393.4   185.6 1384.82   224.7 1378.94   244.2  1376.8     254 1376.11
   322.4 1372.25   439.6 1364.81   449.4 1363.93   459.2 1361.83   474.9 1356.28
   478.7 1355.06   488.5 1355.18   489.9 1355.67   498.3  1358.6   517.8 1367.77
   556.9 1384.21   576.4 1391.72  612.761404.746   625.3 1408.61     635 1410.62
   644.8  1413.3  653.581416.669   683.9 1429.43   693.7 1432.58   732.8 1443.12
#Mann= 5 ,-1 , 0
       0     .12       0   474.9    .045       0   489.9     .12       0
  612.76    .016       0  653.58     .12       0
Bank Sta=474.9,489.9
XS Rating Curve= 0 ,0
Exp/Cntr=0.3,0.1

Type RM Length L Ch R = 1 ,5315.6  ,292.3,307.2,322.1
XS GIS Cut Line= 3
      1848615.48      270463.807     1848677.978      270776.299
     1848812.077      271077.559
#Sta/Elev= 30
       0 1394.41    19.3 1391.76   106.2  1384.6   173.8 1378.18   231.8 1373.01
   241.4 1371.59   289.7 1362.76   299.4 1361.17     309 1360.24     406 1357.78
   415.7 1357.19   425.4 1355.02   445.4 1346.04   454.5 1344.41   460.4 1345.69
   464.2 1346.52   473.9 1352.26   483.6 1359.18   493.3 1365.29   522.4 1381.82
   551.4 1398.73  554.23 1400.09   561.2 1403.44   570.8 1406.38   580.6 1408.68
   590.2 1411.96  595.431414.187   619.3 1424.46     629 1428.01   648.4 1434.61
#Mann= 5 ,-1 , 0
       0     .12       0   445.4    .045       0   460.4     .12       0
  554.23    .016       0  595.43     .12       0
Bank Sta=445.4,460.4
XS Rating Curve= 0 ,0
Exp/Cntr=0.3,0.1

Type RM Length L Ch R = 1 ,5008.3  ,198.5,209.6,220.7
XS GIS Cut Line= 3
     1848534.434      270595.315     1848415.391      271088.799
     1848489.862      271187.724
#Sta/Elev= 30
       0 1380.99    19.5 1379.65      39 1377.72    68.3  1374.5    87.9 1371.91
   117.2 1367.21   175.7 1356.16   195.2 1353.25   224.5 1351.13   283.1 1348.04
   331.9 1346.92   341.7 1346.36   361.2 1343.59     371 1341.34   390.5 1335.71
   394.4 1335.19   400.2 1334.42   409.4 1335.17   419.8 1338.01   439.3 1345.46
   449.1 1348.69   458.8 1351.38   488.1 1357.28   555.3  1372.2  587.011380.113
   593.4 1381.81   612.4 1385.36   621.9 1387.86  625.991389.334   631.5 1391.32
#Mann= 5 ,-1 , 0
       0     .12       0   394.4    .045       0   409.4     .12       0
  587.01    .016       0  625.99     .12       0
Bank Sta=394.4,409.4
XS Rating Curve= 0 ,0
Exp/Cntr=0.3,0.1

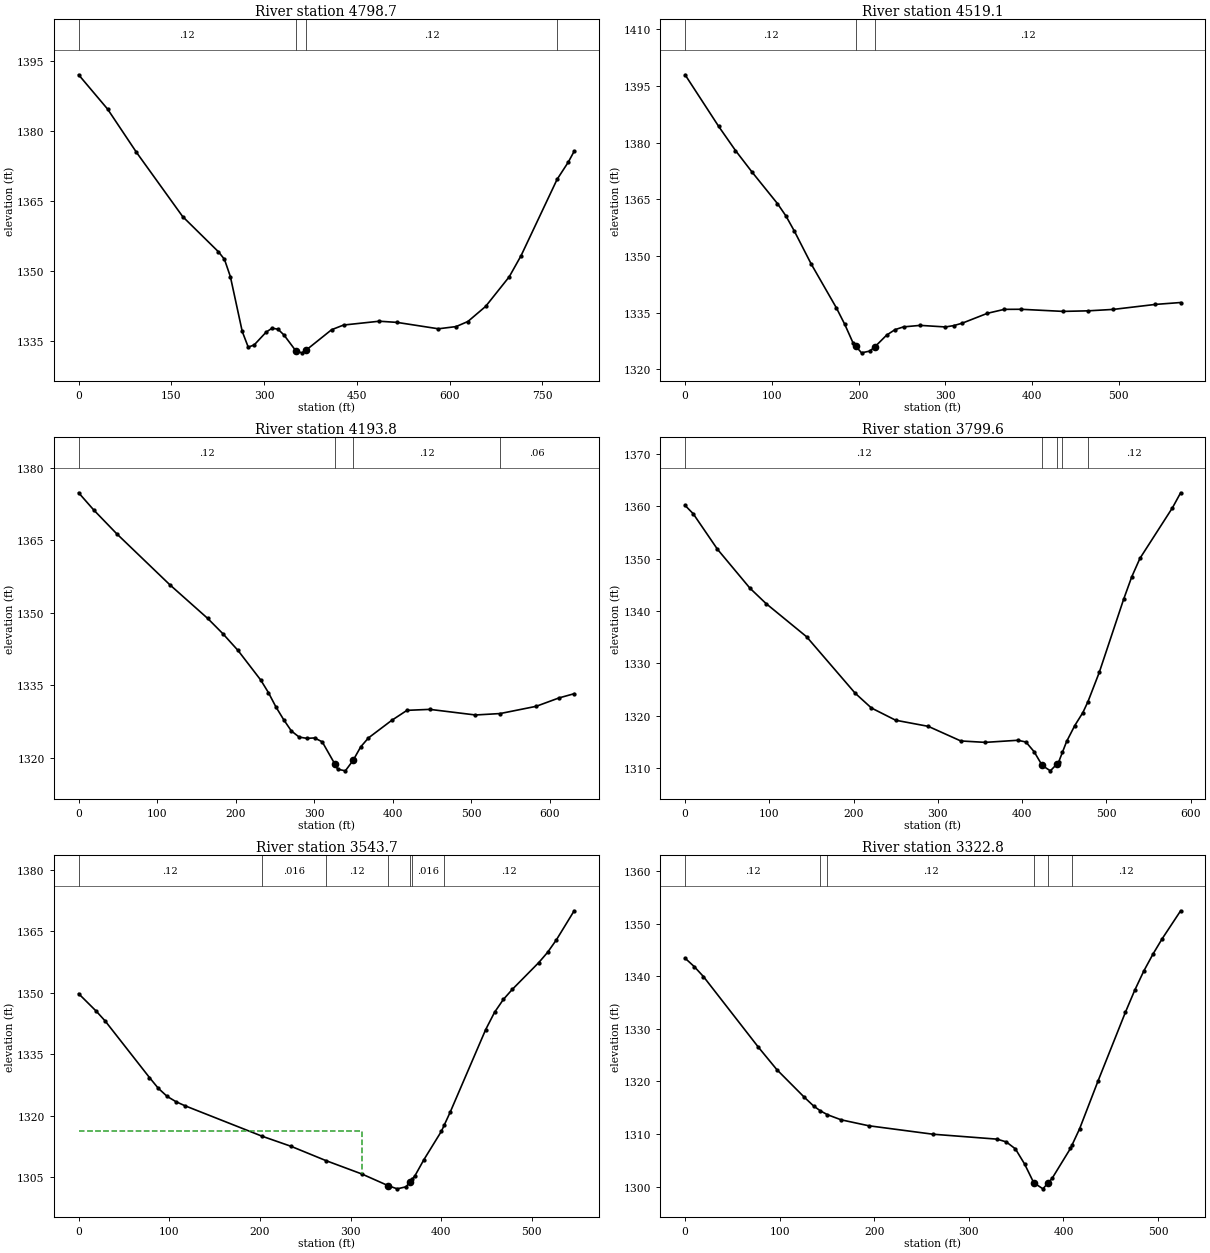
Type RM Length L Ch R = 1 ,4798.7  ,303.3,279.7,256.1
XS GIS Cut Line= 4
     1848399.298       270564.66      1848393.69      270732.897
     1848176.676      270978.122     1848358.944      271223.484
#Sta/Elev= 30
       0 1392.05    46.8 1384.71    93.5 1375.45   168.3 1361.68   226.1 1354.15
   235.8 1352.54   245.4 1348.83   264.6 1337.08   274.3 1333.73   283.9  1334.2
   303.2 1336.94   312.8 1337.79   322.4 1337.57   332.1 1336.33   351.3 1332.93
     361 1332.51   367.5 1333.05   409.1 1337.46   428.4 1338.46   486.2 1339.28
   514.9 1339.03   581.8 1337.66   610.4 1338.13   629.5 1339.22   658.2 1342.45
   696.4  1348.8   715.5 1353.31  773.821369.666   791.9 1373.35   801.4 1375.67
#Mann= 4 ,-1 , 0
       0     .12       0   351.3    .045       0   367.5     .12       0
  773.82    .016       0
Bank Sta=351.3,367.5
XS Rating Curve= 0 ,0
Exp/Cntr=0.3,0.1

Type RM Length L Ch R = 1 ,4519.1  ,347,325.3,303.5
XS GIS Cut Line= 2
     1847952.709      270646.647     1848126.763      271190.796
#Sta/Elev= 30
       0 1397.96    38.7  1384.3    58.1 1377.91    77.5 1372.12   106.5 1363.86
   116.2 1360.61   125.9 1356.61   145.2 1347.95   174.3 1336.31     184 1331.94
   193.7 1326.95   196.8 1326.12   203.4 1324.36     213 1324.83  219.03 1326.01
   232.4 1329.06   242.1 1330.51   251.8 1331.23   271.1 1331.63   300.2 1331.21
   309.9 1331.58   319.6 1332.22   348.6 1334.83     368 1335.87   387.3 1335.89
   435.7 1335.33   464.8 1335.48   493.8 1335.86   542.3 1337.18   571.3 1337.68
#Mann= 3 ,-1 , 0
       0     .12       0   196.8    .045       0  219.03     .12       0
Bank Sta=196.8,219.03
XS Rating Curve= 0 ,0
Exp/Cntr=0.3,0.1

Type RM Length L Ch R = 1 ,4193.8  ,371,394.1,417.3
XS GIS Cut Line= 4
     1847662.715      270778.524     1847751.937      271013.375
     1847910.357      271065.458     1848000.895       271258.07
#Sta/Elev= 30
       0 1374.84    19.3 1371.27    48.3 1366.39     116 1355.82   164.3 1348.84
   183.6 1345.68   202.9 1342.21   231.9 1336.07   241.6 1333.49   251.2 1330.51
     261 1327.89   270.8 1325.55   280.7 1324.29   290.5 1324.02   300.3 1324.11
   310.1  1323.3   325.8 1318.81   329.7 1317.64   339.5  1317.3   349.3 1319.44
   359.1 1322.27   368.9 1324.11   398.4 1327.73     418 1329.82     447 1330.02
   505.1 1328.86  536.591329.154   582.4 1330.65   611.5 1332.39   630.8 1333.26
#Mann= 4 ,-1 , 0
       0     .12       0   325.8    .045       0   349.3     .12       0
  536.59     .06       0
Bank Sta=325.8,349.3
XS Rating Curve= 0 ,0
Exp/Cntr=0.3,0.1

Type RM Length L Ch R = 1 ,3799.6  ,256,255.9,255.4
XS GIS Cut Line= 3
     1847507.759      270855.046     1847510.444       271095.31
     1847588.935      271434.132
#Sta/Elev= 30
       0 1360.17     9.6 1358.59    38.4  1351.8    76.9 1344.37    96.1 1341.42
   144.2 1335.08   201.8  1324.3   221.1 1321.47   249.9 1319.13   288.6 1317.96
   327.2 1315.17   356.2  1314.9   394.8  1315.3   404.5 1314.97   414.2 1313.12
   423.8 1310.49   433.5 1309.46   441.5  1310.8   443.2 1311.09  447.831313.014
   452.8 1315.08   462.5 1318.12   472.1  1320.6  478.141322.692   491.5 1328.26
   520.4 1342.22   530.1 1346.54   539.8 1350.06   578.4 1359.73   588.1 1362.59
#Mann= 5 ,-1 , 0
       0     .12       0   423.8    .045       0   441.5     .12       0
  447.83    .016       0  478.14     .12       0
Bank Sta=423.8,441.5
XS Rating Curve= 0 ,0
Exp/Cntr=0.3,0.1

Type RM Length L Ch R = 1 ,3543.7  ,221,220.9,220.8
XS GIS Cut Line= 2
     1847216.601      270972.289     1847346.076      271503.361
#Sta/Elev= 30
       0 1349.79    19.5 1345.51    29.3 1343.13    78.1 1329.35    87.8 1326.74
    97.6 1324.75   107.4 1323.45   117.1 1322.48  202.491315.023   234.3 1312.57
  273.221309.047   312.4 1305.82   341.6 1302.96   351.4  1302.2   361.2  1302.7
   365.6 1303.91  367.911304.542   370.9 1305.36   380.7 1309.26   400.2 1316.26
   403.11317.657     410 1320.98     449 1341.04   458.8 1345.26   468.5 1348.39
   478.3 1350.83   507.6 1357.39   517.3 1359.88   527.1 1362.96   546.6 1370.01
#Mann= 7 ,-1 , 0
       0     .12       0  202.49    .016       0  273.22     .12       0
   341.6    .045       0   365.6     .12       0  367.91    .016       0
   403.1     .12       0
#XS Ineff= 2 , 0
          312.72 1316.29
Permanent Ineff=
       F       F
Bank Sta=341.6,365.6
XS Rating Curve= 0 ,0
Exp/Cntr=0.3,0.1

Type RM Length L Ch R = 1 ,3322.8  ,198.3,209.2,220.1
XS GIS Cut Line= 3
     1847104.151      270992.759     1847067.258      271281.387
     1847124.678      271507.082
#Sta/Elev= 30
       0 1343.42     9.7 1341.82    19.4 1339.93    77.6 1326.47      97 1322.23
   126.1 1316.97   135.8 1315.33  143.031314.391  150.541313.654   164.9 1312.69
     194 1311.56   261.9 1309.95   329.8 1309.01   339.5 1308.49   349.2 1307.16
   358.9 1304.29   368.6 1300.72   378.3 1299.56   383.6 1300.65     388 1301.55
   407.4 1307.24  409.151307.917   417.1 1310.99   436.5 1320.04   465.6 1333.18
   475.3  1337.3     485    1341   494.8 1344.25   504.4 1347.13   523.9 1352.44
#Mann= 6 ,-1 , 0
       0     .12       0  143.03     .06       0  150.54     .12       0
   368.6    .045       0   383.6    .016       0  409.15     .12       0
Bank Sta=368.6,383.6
XS Rating Curve= 0 ,0
Exp/Cntr=0.3,0.1

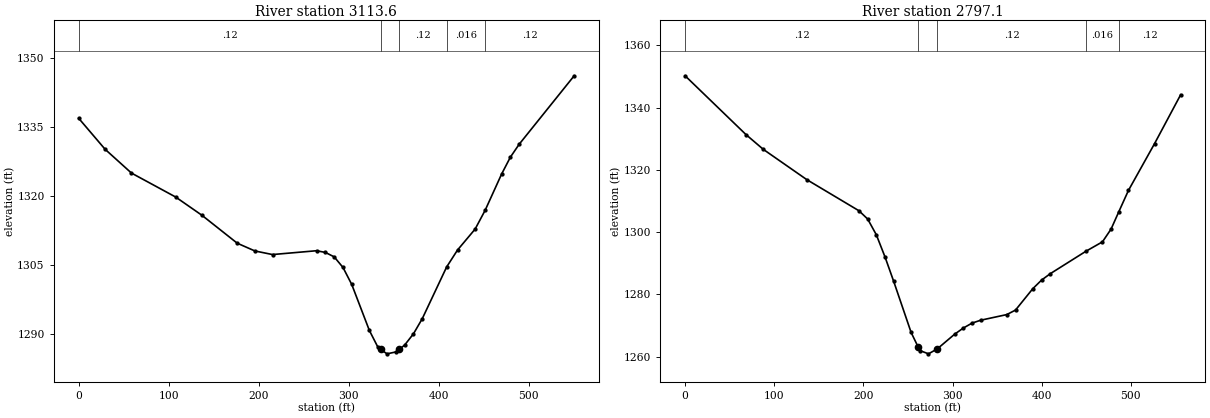
Type RM Length L Ch R = 1 ,3113.6  ,330.9,316.5,302.1
XS GIS Cut Line= 3
     1846969.396      270976.626     1846852.891      271462.063
      1846866.85      271511.416
#Sta/Elev= 30
       0 1336.85    29.4 1330.12    58.7 1324.96   107.7 1319.78     137 1315.81
   176.2 1309.76   195.8 1308.08   215.4  1307.3   264.3 1308.13   274.1 1307.76
   283.9  1306.8   293.7  1304.5   303.4 1300.82     323 1290.84   332.6 1287.17
  335.61 1286.74   342.6 1285.78   352.4 1286.19  356.37 1286.77   362.2 1287.69
     372 1290.13   381.8 1293.42  408.811304.604   420.9 1308.28   440.5 1312.83
  451.651316.914   469.9 1324.75   479.6  1328.4   489.4 1331.21   550.5 1346.05
#Mann= 5 ,-1 , 0
       0     .12       0  335.61    .045       0  356.37     .12       0
  408.81    .016       0  451.65     .12       0
Bank Sta=335.61,356.37
XS Rating Curve= 0 ,0
Exp/Cntr=0.3,0.1

Type RM Length L Ch R = 1 ,2797.1  ,215.9,216.3,216.7
XS GIS Cut Line= 2
     1846500.106      271011.385     1846712.146      271525.174
#Sta/Elev= 30
       0  1350.2    68.3 1331.32    87.8 1326.56   136.5 1316.86     195 1306.87
   204.8 1304.21   214.5 1299.15   224.3 1291.99     234 1284.17   253.5 1267.81
   261.6 1263.01   263.3    1262     273 1260.94   282.8 1262.52   302.3 1267.24
     312 1269.21   321.8  1270.8   331.5 1271.73   360.8 1273.54   370.6 1274.99
     390 1281.86   399.8 1284.61   409.6 1286.67  449.671293.886   468.1 1296.89
   477.8    1301  486.551306.616   497.3 1313.42   526.6 1328.45   555.8  1344.1
#Mann= 5 ,-1 , 0
       0     .12       0   261.6    .045       0   282.8     .12       0
  449.67    .016       0  486.55     .12       0
Bank Sta=261.6,282.8
XS Rating Curve= 0 ,0
Exp/Cntr=0.3,0.1