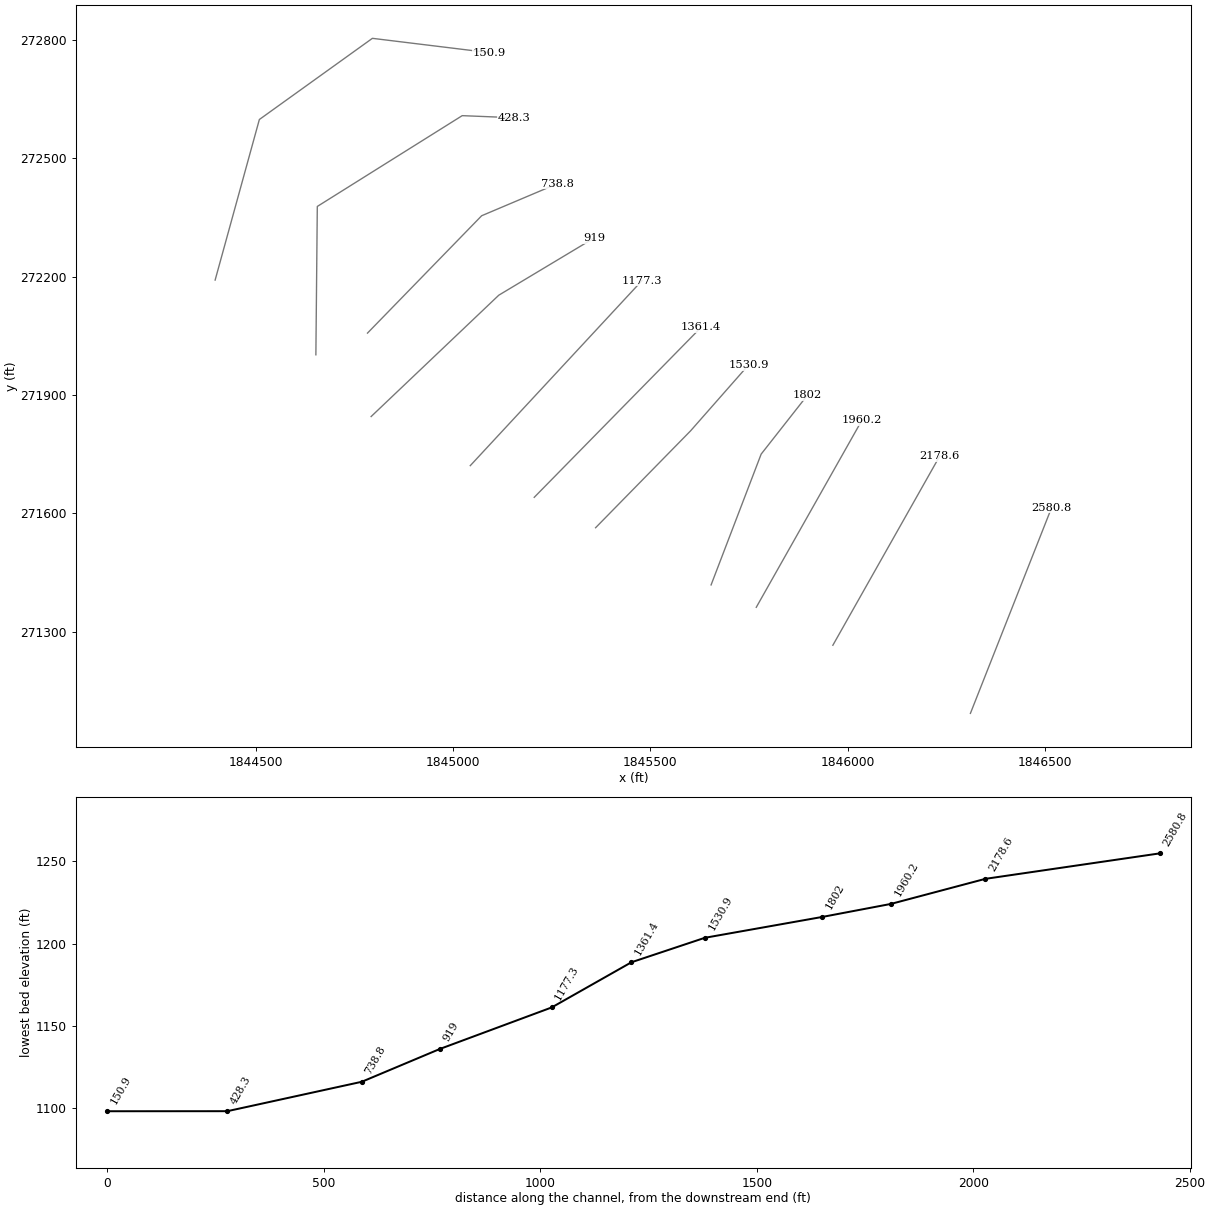
HEC-RAS study BIGCOVERN.prj: BIGCOVERN

--- BIGCOVERN.g01 (geometry) --- (continued)

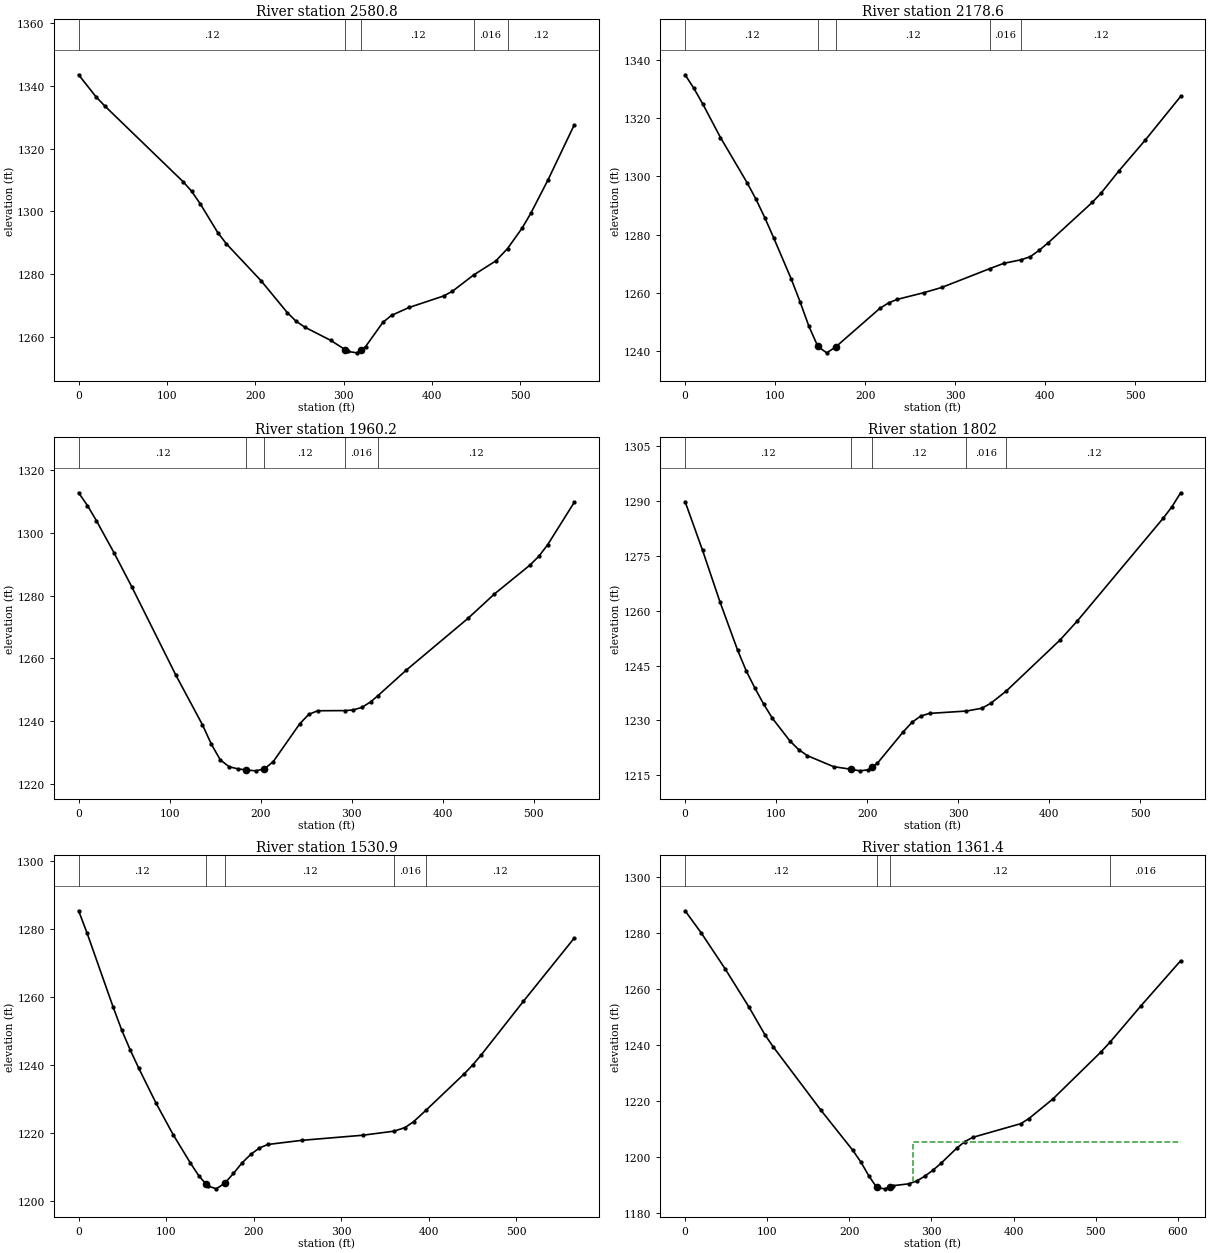
Type RM Length L Ch R = 1 ,2580.8  ,405.1,402.2,399.3
XS GIS Cut Line= 2
      1846311.15       271093.14     1846517.039      271614.818
#Sta/Elev= 30
       0 1343.51    19.7 1336.48    29.5  1333.6   118.1 1309.48   127.9 1306.39
   137.8 1302.32   157.4 1293.25   167.3 1289.62   206.6 1277.84   236.1 1267.74
     246    1265   255.8 1263.12   285.3 1258.88  301.47 1255.96     305 1255.35
   314.9 1254.91     320 1255.94   324.7 1256.88   344.4 1264.65   354.2 1266.86
   373.9 1269.36   413.2 1273.04   423.1 1274.55  446.89 1279.69   472.3 1284.24
  485.371288.136   501.8 1294.62   511.6 1299.32   531.3 1310.08   560.8  1327.5
#Mann= 5 ,-1 , 0
       0     .12       0  301.47    .045       0     320     .12       0
  446.89    .016       0  485.37     .12       0
Bank Sta=301.47,320
XS Rating Curve= 0 ,0
Exp/Cntr=0.3,0.1

Type RM Length L Ch R = 1 ,2178.6  ,218,218.4,218
XS GIS Cut Line= 2
     1845962.579      271265.817     1846233.318      271745.176
#Sta/Elev= 30
       0  1334.8     9.8 1330.12    19.7 1324.75    39.3 1313.28    68.8 1297.81
    78.6  1292.2    88.5  1285.8    98.3 1278.95     118 1264.68   127.8 1256.85
   137.6 1248.47   147.5 1241.59   157.3 1239.41   167.1 1241.38   216.3 1254.65
   226.1 1256.56   235.9 1257.77   265.4 1260.06   285.1 1261.84  338.211268.266
   353.9  1270.1   373.4 1271.35   383.4 1272.39   393.2 1274.55   403.1 1277.09
   452.2 1290.99     462 1294.16   481.7 1301.75   511.2  1312.4   550.5 1327.38
#Mann= 5 ,-1 , 0
       0     .12       0   147.5    .045       0   167.1     .12       0
  338.21    .016       0   373.4     .12       0
Bank Sta=147.5,167.1
XS Rating Curve= 0 ,0
Exp/Cntr=0.3,0.1

Type RM Length L Ch R = 1 ,1960.2  ,155,158.2,161.7
XS GIS Cut Line= 2
     1845768.455      271361.983     1846036.066      271835.805
#Sta/Elev= 30
       0 1312.77     9.7  1308.7    19.4 1303.93    38.9 1293.63    58.3 1282.83
   106.9 1254.55     136 1238.78   145.8 1232.58   155.5 1227.64   165.2 1225.42
   174.9 1224.74   184.2 1224.39   194.4 1224.11   204.1 1224.72   213.8 1227.08
   242.9 1239.14   252.6 1242.08   262.4 1243.27  292.251243.316   301.2 1243.51
     311 1244.33   320.7  1246.1   328.71248.079   359.5 1256.14   427.6 1272.73
   456.7 1280.52   495.6  1289.7   505.3 1292.49     515 1296.17   544.2 1309.68
#Mann= 5 ,-1 , 0
       0     .12       0   184.2    .045       0   204.1     .12       0
  292.25    .016       0   328.7     .12       0
Bank Sta=184.2,204.1
XS Rating Curve= 0 ,0
Exp/Cntr=0.3,0.1

Type RM Length L Ch R = 1 ,1802    ,280.4,271.2,261.8
XS GIS Cut Line= 3
     1845653.965        271418.7     1845780.843      271750.258
     1845897.927      271899.274
#Sta/Elev= 30
       0 1289.88    19.2 1276.54    38.4 1262.38    57.6 1249.29    67.2 1243.54
    76.8 1238.78    86.4 1234.42      96 1230.55   115.1  1224.4   124.7 1222.03
   134.3 1220.35   163.1 1217.34   182.3 1216.62   191.9 1216.19   201.5 1216.48
     205 1217.11   211.1 1218.21   239.9 1226.92   249.5 1229.51   259.1 1231.21
   268.6 1231.91   309.21232.559   326.2 1233.33   335.8 1234.67  353.011238.054
   411.9 1251.98   430.8 1257.16   525.6 1285.42     535 1288.49   544.5  1292.3
#Mann= 5 ,-1 , 0
       0     .12       0   182.3    .045       0     205     .12       0
   309.2    .016       0  353.01     .12       0
Bank Sta=182.3,205
XS Rating Curve= 0 ,0
Exp/Cntr=0.3,0.1

Type RM Length L Ch R = 1 ,1530.9  ,169.5,169.5,169.4
XS GIS Cut Line= 3
     1845361.272      271563.695     1845602.023      271809.286
     1845748.805      271976.111
#Sta/Elev= 30
       0 1285.26     9.8 1278.59    39.3 1257.03    49.1 1250.26      59 1244.28
    68.8  1238.9    88.4  1228.7   108.1 1219.37   127.7 1211.07   137.6  1207.2
   145.4 1204.96   147.4 1204.38   157.2 1203.48     167 1205.15   176.9 1208.02
   186.7 1211.11   196.5 1213.58   206.4 1215.48   216.2 1216.53   255.5 1217.76
   324.3 1219.24   360.41220.445   372.9 1221.51   382.6 1223.21  396.771226.587
   440.5  1237.3   450.2 1239.91   459.8 1242.83   508.2 1258.67   566.1  1277.2
#Mann= 5 ,-1 , 0
       0     .12       0   145.4    .045       0     167     .12       0
   360.4    .016       0  396.77     .12       0
Bank Sta=145.4,167
XS Rating Curve= 0 ,0
Exp/Cntr=0.3,0.1

Type RM Length L Ch R = 1 ,1361.4  ,183.4,184.1,184.7
XS GIS Cut Line= 2
     1845205.745      271640.741      1845628.47      272071.441
#Sta/Elev= 30
       0 1287.84    19.5    1280    48.7 1267.14    77.9 1253.42    97.3 1243.54
   107.1 1239.36   165.5 1216.61   204.4 1202.26   214.1 1198.12   223.9 1193.13
  233.11 1189.19   233.6 1188.99   243.3 1188.57   249.1 1189.23   253.1 1189.69
   272.5 1190.36   282.3 1191.41     292  1193.1   301.7 1195.18   311.5 1197.64
     331 1203.15   340.7 1205.45   350.4 1206.96   408.8 1211.84   418.6 1213.63
   447.8 1220.62   506.2 1237.36  517.561240.948   554.8 1253.78   603.5    1270
#Mann= 4 ,-1 , 0
       0     .12       0  233.11    .045       0   249.1     .12       0
  517.56    .016       0
#XS Ineff= 2 , 0
                          277.39         1205.43
Permanent Ineff=
       F       F
Bank Sta=233.11,249.1
XS Rating Curve= 0 ,0
Exp/Cntr=0.3,0.1

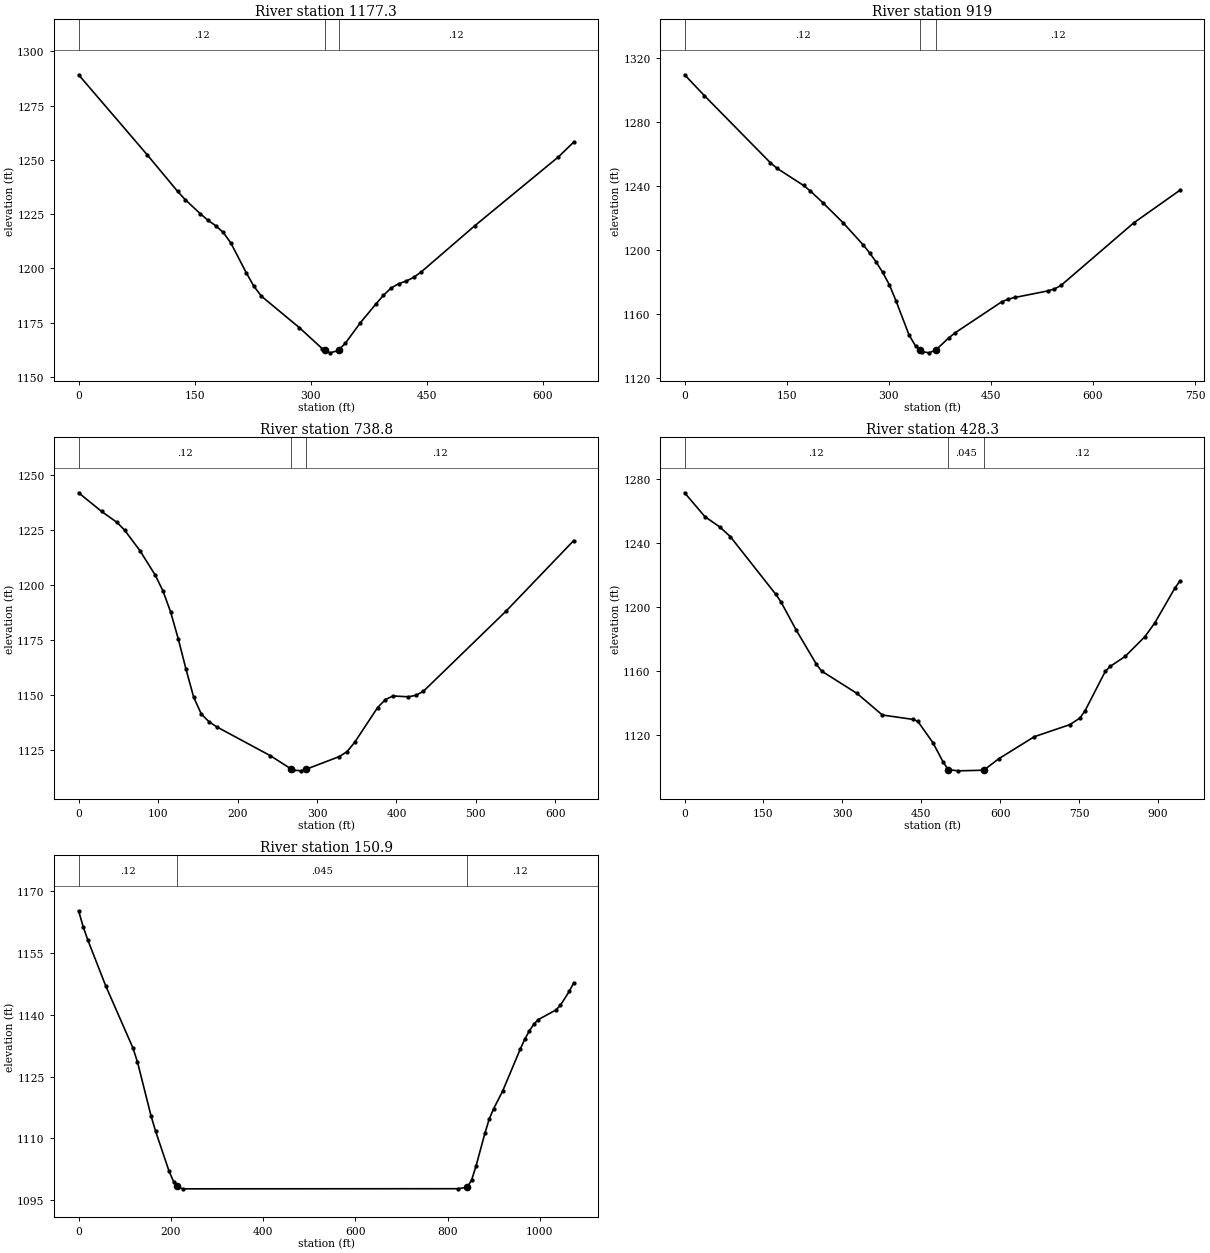
Type RM Length L Ch R = 1 ,1177.3  ,259.7,258.3,256.5
XS GIS Cut Line= 2
     1845043.659      271721.036     1845478.803      272190.009
#Sta/Elev= 30
       0 1289.18    88.6 1252.32     128 1235.42   137.8 1231.63   157.5 1225.06
   167.3 1222.09   177.2 1219.61     187  1216.5   196.8 1211.61   216.5 1198.05
   226.4 1191.77   236.2 1187.16   285.4  1172.6     315 1162.92  317.87  1162.3
   324.8 1161.04   334.6 1161.98  336.39 1162.55   344.5 1165.37   364.2 1174.95
   383.8 1183.38   393.7 1187.47   403.5 1190.82   413.4 1192.88   423.2 1194.08
   433.1 1195.84   442.9 1198.37   511.8 1219.56   620.1 1251.36   639.8 1258.16
#Mann= 3 ,-1 , 0
       0     .12       0  317.87    .045       0  336.39     .12       0
Bank Sta=317.87,336.39
XS Rating Curve= 0 ,0
Exp/Cntr=0.3,0.1

Type RM Length L Ch R = 1 ,919     ,179.5,180.3,181
XS GIS Cut Line= 3
     1844792.409      271845.501     1845115.912      272153.036
     1845356.896      272297.626
#Sta/Elev= 30
       0  1309.4    29.1 1296.37   126.1 1254.43   135.8 1250.99   174.7 1240.28
   184.4 1236.95   203.8 1229.22   232.9 1216.97     262 1203.33   271.7 1198.27
   281.4 1192.47   291.1 1185.92   300.8 1178.27   310.5 1168.31   329.9 1146.74
   339.6 1139.84  346.31 1137.47   349.3 1136.53     359 1135.73     369 1137.44
   388.1 1145.08   397.8 1148.34   465.7 1167.55   475.4 1169.26   485.1  1170.3
   533.6 1174.41   543.3 1175.61     553 1177.83   659.6 1216.81   727.4 1237.19
#Mann= 3 ,-1 , 0
       0     .12       0  346.31    .045       0     369     .12       0
Bank Sta=346.31,369
XS Rating Curve= 0 ,0
Exp/Cntr=0.3,0.1

Type RM Length L Ch R = 1 ,738.8   ,315.7,310.5,305
XS GIS Cut Line= 3
     1844783.187      272056.995     1845072.509      272354.424
     1845264.189      272435.556
#Sta/Elev= 30
       0 1242.04      29 1233.55    48.2 1228.61    57.9 1225.07    77.2 1215.74
    96.5 1204.61   106.2 1197.41   115.8 1187.89   125.4 1175.69   135.1 1161.99
   144.8 1149.18   154.4 1141.56     164 1138.05   173.7 1135.74   241.2 1122.63
  266.74 1116.75   270.2 1116.09   279.8 1115.73   286.5 1116.47   328.1 1122.21
   337.7 1124.42   347.4 1128.67   376.3 1144.48     386 1148.06   395.6 1149.74
   414.9 1149.37   424.4 1150.01   433.9 1151.86   537.9 1188.27   623.1 1220.34
#Mann= 3 ,-1 , 0
       0     .12       0  266.74    .045       0   286.5     .12       0
Bank Sta=266.74,286.5
XS Rating Curve= 0 ,0
Exp/Cntr=0.3,0.1

Type RM Length L Ch R = 1 ,428.3   ,275.9,277.3,278.7
XS GIS Cut Line= 4
     1844652.371      272001.994     1844655.987      272377.983
     1845023.233      272608.109     1845154.999      272602.788
#Sta/Elev= 30
       0 1271.19    38.6 1256.31    67.5 1249.73    86.8  1243.9   173.5 1207.83
   183.2 1203.16   212.1 1185.65   250.7 1164.23   260.3 1160.04   327.8 1146.09
     376 1132.62   433.8  1129.9   443.4 1128.66   472.3 1115.27   491.6 1103.28
   501.2 1098.56   520.5 1097.81   568.6  1098.2   597.5 1105.38   664.9 1119.11
   732.4 1126.61   751.6 1130.73   761.2 1135.18   799.8 1159.81   809.4 1162.99
   837.7 1169.19   875.3 1181.52   894.2 1190.17   931.8 1211.56   941.3 1216.01
#Mann= 3 ,-1 , 0
       0     .12       0   501.2    .045       0   568.6     .12       0
Bank Sta=501.2,568.6
XS Rating Curve= 0 ,0
Exp/Cntr=0.3,0.1

Type RM Length L Ch R = 1 ,150.9   ,151.6,150.9,150.3
XS GIS Cut Line= 4
      1844397.04       272191.37     1844509.141      272598.348
       1844795.6      272804.077     1845091.953      272767.821
#Sta/Elev= 30
       0 1165.19     9.8 1161.36    19.6 1158.21    58.9 1146.95   117.8 1131.93
   127.6 1128.54   157.1 1115.44   166.9 1111.74   196.3    1102   206.2 1099.46
  213.551098.485     216 1098.16   225.8 1097.78     823 1097.81   842.2 1098.17
   851.9 1099.86   861.5 1103.27   880.8 1111.24   890.4 1114.76     900 1117.25
   919.3 1121.48   957.8 1131.73   967.4 1134.07   977.1 1136.06   986.7 1137.66
   996.3 1138.79  1034.8 1141.14  1044.5 1142.28  1063.8 1145.66  1073.4 1147.73
#Mann= 3 ,-1 , 0
       0     .12       0  213.55    .045       0   842.2     .12       0
Bank Sta=213.55,842.2
XS Rating Curve= 0 ,0
Exp/Cntr=0.3,0.1

Chan Stop Cuts=-1
Use User Specified Reach Order=0
Composite Channel Slope=5